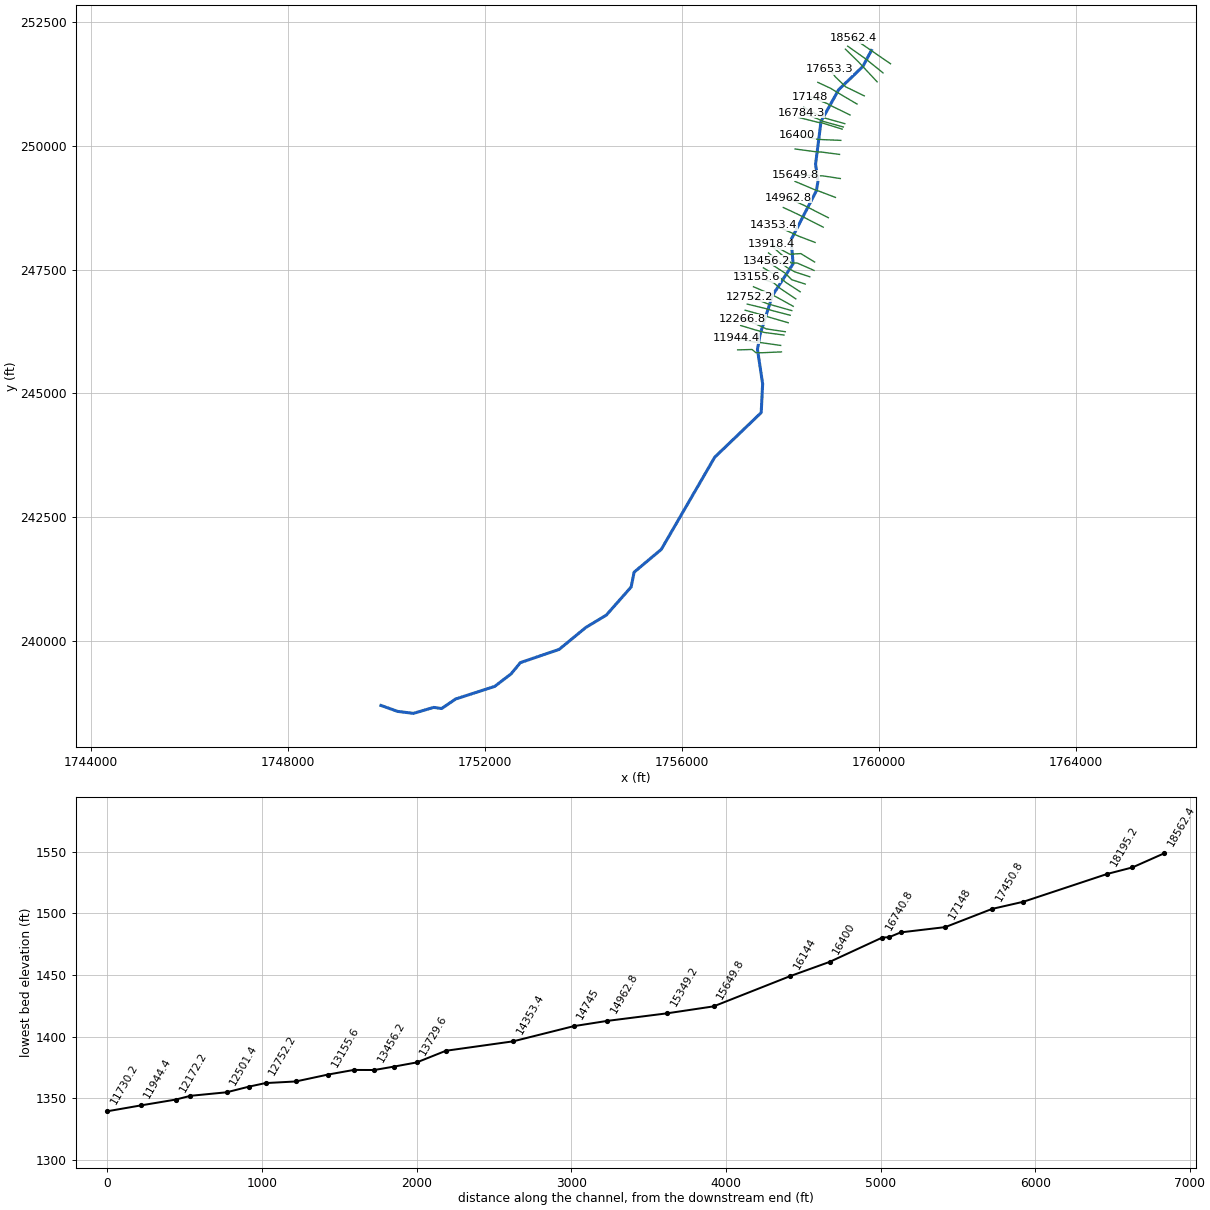
--- BigCubCr.prj (project) ---

Proj Title=BigCubCr
Current Plan=p01
Default Exp/Contr=0,0
English Units
Geom File=g01
Flow File=f01
Plan File=p01
BEGIN DESCRIPTION:
END DESCRIPTION:
DSS Export Rating Curves= 0
DSS Export Rating Curve Sorted= 0
DSS Export Volume Flow Curves= 0
DXF OffsetX= 0
DXF OffsetY= 0
DXF ScaleX= 0
DXF ScaleY= 0

--- BigCubCr.p01 (plan) ---

Plan Title=Floodplain
Program Version=4.00
Geom File=g01
Flow File=f01
K Sum by GR=0
Std Step Tol=0.01
Critical Tol=0.01
Num of Std Step Trials=20
Max Error Tol=0.3
Flow Tol Ratio=0.001
Split Flow NTrial=30
Split Flow Tol=0.02
Split Flow Ratio=0.02
Log Output Level=0
Friction Slope Method=1
Unsteady Friction Slope Method=2
Unsteady Bridges Friction Slope Method=1
Global Log Level=0
CheckData=False
Run HTab=0
Run UNet=0
Run PostProcess=0
UNET Theta=0
UNET Theta Warmup=0
UNET ZTol=0
UNET ZSATol=0
UNET MxIter=0
UNET MaxInSteps=0
UNET DtIC=0
UNET DtMin=0
UNET MaxCRTS=0
UNET WFStab=0
UNET SFStab=0
UNET WFX=0
UNET SFX=0
UNET DSS MLevel=0
UNET DZMax Abort=0
UNET Convert EG Bridges=0
UNET Use Existing IB Tables=0
UNET Froude Limit=0
UNET Froude Power=0
Write IC File=0
Echo Input=False
Echo Output=False
Write Detailed=0

--- BigCubCr.f01 (steady flow) ---

Flow Title=NFF Regression Equation
Program Version=4.00
Number of Profiles=1
Profile Names=P100yr
River Rch & RM=BigCubCr,Main      ,18562.4
548.7863
River Rch & RM=BigCubCr,Main      ,18358.2
593.2301
River Rch & RM=BigCubCr,Main      ,17450.8
604.7986
River Rch & RM=BigCubCr,Main      ,16860.1
687.6591
River Rch & RM=BigCubCr,Main      ,15349.2
748.6820
River Rch & RM=BigCubCr,Main      ,15349.2
982.2596
River Rch & RM=BigCubCr,Main      ,14745
990.4916
River Rch & RM=BigCubCr,Main      ,11730.2
1081.810
River Rch & RM=BigCubCr,Main      ,11004.8
1204.780
River Rch & RM=BigCubCr,Main      ,10528.7
1209.907
River Rch & RM=BigCubCr,Main      ,10227.1
1501.889
River Rch & RM=BigCubCr,Main      ,7223.6
1600.450
River Rch & RM=BigCubCr,Main      ,6926.8
1782.665
River Rch & RM=BigCubCr,Main      ,5127.3
1811.821
River Rch & RM=BigCubCr,Main      ,312.6
1976.687
Boundary for River Rch & Prof#=BigCubCr,Main      ,1
Up Type=0
Dn Type=3
Dn Slope=0.008587

--- BigCubCr.g01 (geometry) ---

Geom Title=USGS 10m DEM
Program Version=4.00

River Reach=BigCubCr        ,Main
Reach XY= 30
     1759849.108      251931.782     1759675.114      251607.312
     1759183.974      251137.805     1758825.559      250498.739
     1758715.637      249632.228     1758763.582      249282.584
     1758731.424      249094.898     1758216.897      248103.848
     1758259.579      247620.309     1757837.231      246974.555
     1757589.524      246195.419     1757535.148      245888.457
     1757640.239      245190.522     1757610.968      244609.435
     1756666.298      243706.978     1755581.704      241844.236
     1755030.273      241383.862     1754969.559       241084.34
     1754464.957      240515.426     1754048.504      240265.374
     1753507.025      239822.387     1752719.541      239554.795
     1752529.753       239326.78       1752198.1      239074.071
      1751404.07      238819.031     1751120.248      238626.627
     1750958.542      238649.246     1750545.535       238528.67
     1750226.582      238568.396      1749887.08      238689.258

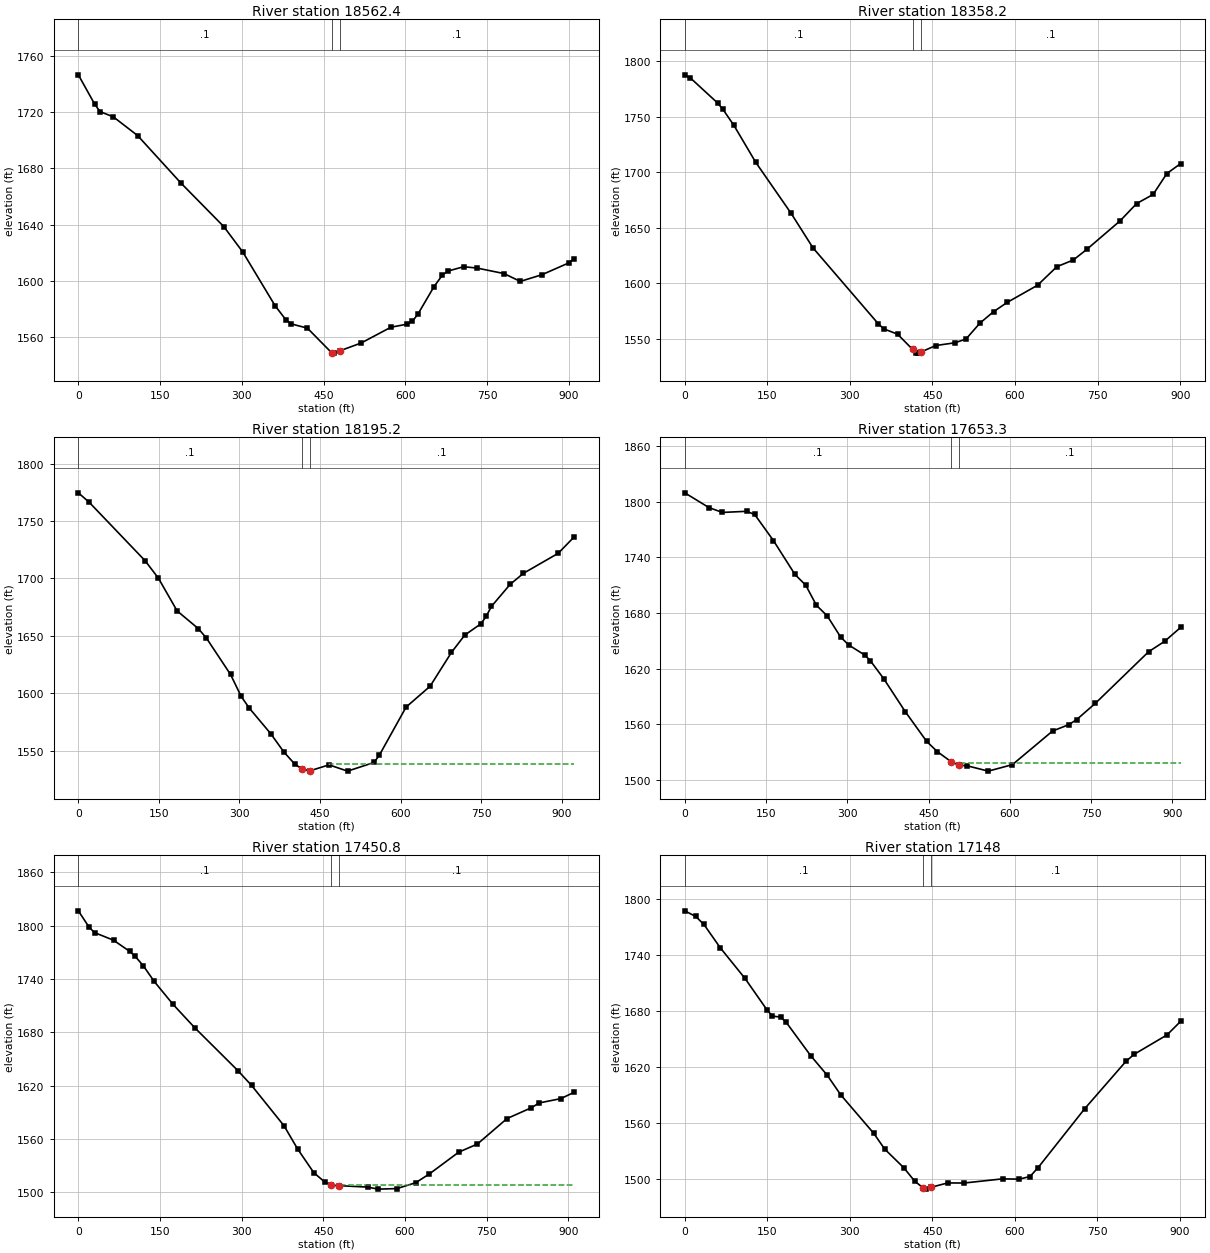
Type RM Length L Ch R = 1 ,18562.4 ,208.5,204.2,205.9
XS GIS Cut Line= 3
     1760237.555      251662.716     1759862.139      251919.792
     1759486.724      252176.868
#Sta/Elev= 30
       0 1746.41    29.7 1725.79    39.6 1720.36    64.3 1716.54   108.8 1703.29
   187.9 1669.73   267.1 1638.58   301.7 1620.68     361 1582.54   380.8 1572.54
   390.7 1569.57   420.4 1566.57   464.7 1549.16   469.8 1548.82   479.7 1550.42
   519.3 1556.05   573.7 1567.22   603.4 1569.38   613.3 1571.53   623.2 1576.48
   652.8 1596.04   667.7 1603.97   677.6 1606.99   707.2 1610.18     732  1609.2
   781.4 1605.29   811.1 1599.74   850.6 1604.45   900.1 1612.86     910 1615.96
#Mann= 3 , 0 , 0
       0      .1       0   464.7    .045       0   479.7      .1       0
Bank Sta=464.7,479.7
XS Rating Curve= 0 ,0
Exp/Cntr=0.3,0.1

Type RM Length L Ch R = 1 ,18358.2 ,163.5,163,156.2
XS GIS Cut Line= 5
     1760085.408      251478.217     1759780.466      251723.705
     1759770.183      251739.917     1759731.014      251762.701
      1759367.22      252018.698
#Sta/Elev= 30
       0 1787.46     9.9 1784.77    59.5 1762.19    69.4 1756.34    89.2 1742.07
   128.8  1708.9   193.3  1662.9   232.9 1631.98   351.8 1563.61   361.8 1559.16
   386.5 1554.47     414 1540.68   419.7 1537.82   424.3 1537.42     429 1538.42
     456 1544.24     491 1546.73     511 1550.15     536 1564.29     561 1574.68
   585.9 1583.04   640.9 1598.42   675.9 1615.06   705.9 1621.11   730.9 1630.86
   790.9 1656.29   820.9 1671.82   850.8 1679.96   875.8 1698.79   900.8  1707.7
#Mann= 3 , 0 , 0
       0      .1       0     414    .045       0     429      .1       0
Bank Sta=414,429
XS Rating Curve= 0 ,0
Exp/Cntr=0.3,0.1

Type RM Length L Ch R = 1 ,18195.2 ,540.8,541.8,543.1
XS GIS Cut Line= 4
     1759965.578      251298.144     1759699.939      251580.642
     1759591.738      251695.712     1759321.032       251958.77
#Sta/Elev= 30
       0 1774.58    19.9  1766.5   124.3 1715.44   149.1 1700.22   183.9 1671.73
   223.7 1656.15   238.6 1647.94   283.4 1616.32   303.3 1597.15   318.2 1587.07
     358 1564.88   382.8 1548.74   402.6 1538.46   416.7  1533.8   431.7 1532.48
   466.8 1537.58   501.3 1532.12   550.7 1539.68   560.6 1546.12   610.3 1587.93
     655 1606.09   694.7 1635.54   719.6 1650.68   749.4  1660.4   759.3 1666.87
   769.2 1675.64     804 1694.83   828.8 1704.47   893.4 1721.86   923.2 1736.18
#Mann= 3 , 0 , 0
       0      .1       0   416.7    .045       0   431.7      .1       0
#XS Ineff= 2 , 0
                          466.78         1538.07
Permanent Ineff=
       F       F
Bank Sta=416.7,431.7
XS Rating Curve= 0 ,0
Exp/Cntr=0.3,0.1

Type RM Length L Ch R = 1 ,17653.3 ,197.6,202.6,207.5
XS GIS Cut Line= 4
     1759705.326      251013.046     1759325.973      251197.346
     1759119.063      251396.332     1758989.957      251557.724
#Sta/Elev= 30
       0 1809.63    44.7 1793.67    69.5  1788.5   114.1 1789.69     129  1786.3
   163.7 1758.11   203.4 1721.61   223.3 1710.03   243.1 1688.27     263 1676.95
   287.8 1654.06   302.7 1645.53   332.4 1634.64   342.4 1628.75   367.2 1609.29
   406.9  1573.8   446.5 1541.65   466.3 1530.54   491.3 1519.88   506.3 1515.84
   520.7 1515.38   560.3 1509.53   604.9 1516.51   679.1  1552.8   708.8 1559.57
   723.6 1565.12     758 1582.61   856.4 1638.28     886 1649.52   915.5 1664.46
#Mann= 3 , 0 , 0
       0      .1       0   491.3    .045       0   506.3      .1       0
#XS Ineff= 2 , 0
                          511.07         1518.21
Permanent Ineff=
       F       F
Bank Sta=491.3,506.3
XS Rating Curve= 0 ,0
Exp/Cntr=0.3,0.1

Type RM Length L Ch R = 1 ,17450.8 ,301.5,302.7,303.6
XS GIS Cut Line= 4
     1759558.176      250847.564     1759172.341      251074.581
     1759021.003      251166.513     1758761.162      251286.732
#Sta/Elev= 30
       0 1816.81    19.9 1798.31    29.8  1792.3    64.7 1783.74    94.5 1771.13
   104.5 1765.54   119.4    1755   139.3 1737.45   174.1  1711.5   213.9 1685.27
   293.5 1636.82   318.3 1620.36     378 1574.92   402.9 1548.88   432.7 1522.15
   452.6  1511.8   464.4 1508.27   479.4 1507.61   531.3    1506     551 1503.71
   585.4 1504.32   619.8  1510.9   644.5 1520.58   698.8 1545.25   733.3 1554.49
   787.6 1583.08   832.1  1595.2   846.9  1600.7   886.4 1605.51     911 1612.68
#Mann= 3 , 0 , 0
       0      .1       0   464.4    .045       0   479.4      .1       0
#XS Ineff= 2 , 0
                          482.03         1507.85
Permanent Ineff=
       F       F
Bank Sta=464.4,479.4
XS Rating Curve= 0 ,0
Exp/Cntr=0.3,0.1

Type RM Length L Ch R = 1 ,17148   ,285.2,288,291.1
XS GIS Cut Line= 4
      1759416.91      250626.807      1759036.31      250811.337
     1758953.402      250857.586     1758595.898      250996.327
#Sta/Elev= 30
       0  1787.4    19.9 1781.32    34.8 1772.76    64.7  1747.6   109.5 1714.86
   149.3 1681.27   159.2 1674.54   174.2 1673.39   184.1 1668.04   228.9 1632.03
   258.8 1611.17   283.6 1589.96   343.4 1548.85   363.3 1531.94   398.1 1511.87
     418 1497.45   432.5 1490.64     438 1488.92   447.5 1490.88   477.9 1495.56
   507.9 1495.47   577.7 1499.94   607.6 1499.63   627.5  1502.4   642.4 1512.07
   727.1 1575.22   801.8 1625.83   816.7 1633.44   876.5 1654.25   901.4 1668.83
#Mann= 3 , 0 , 0
       0      .1       0   432.5    .045       0   447.5      .1       0
Bank Sta=432.5,447.5
XS Rating Curve= 0 ,0
Exp/Cntr=0.3,0.1

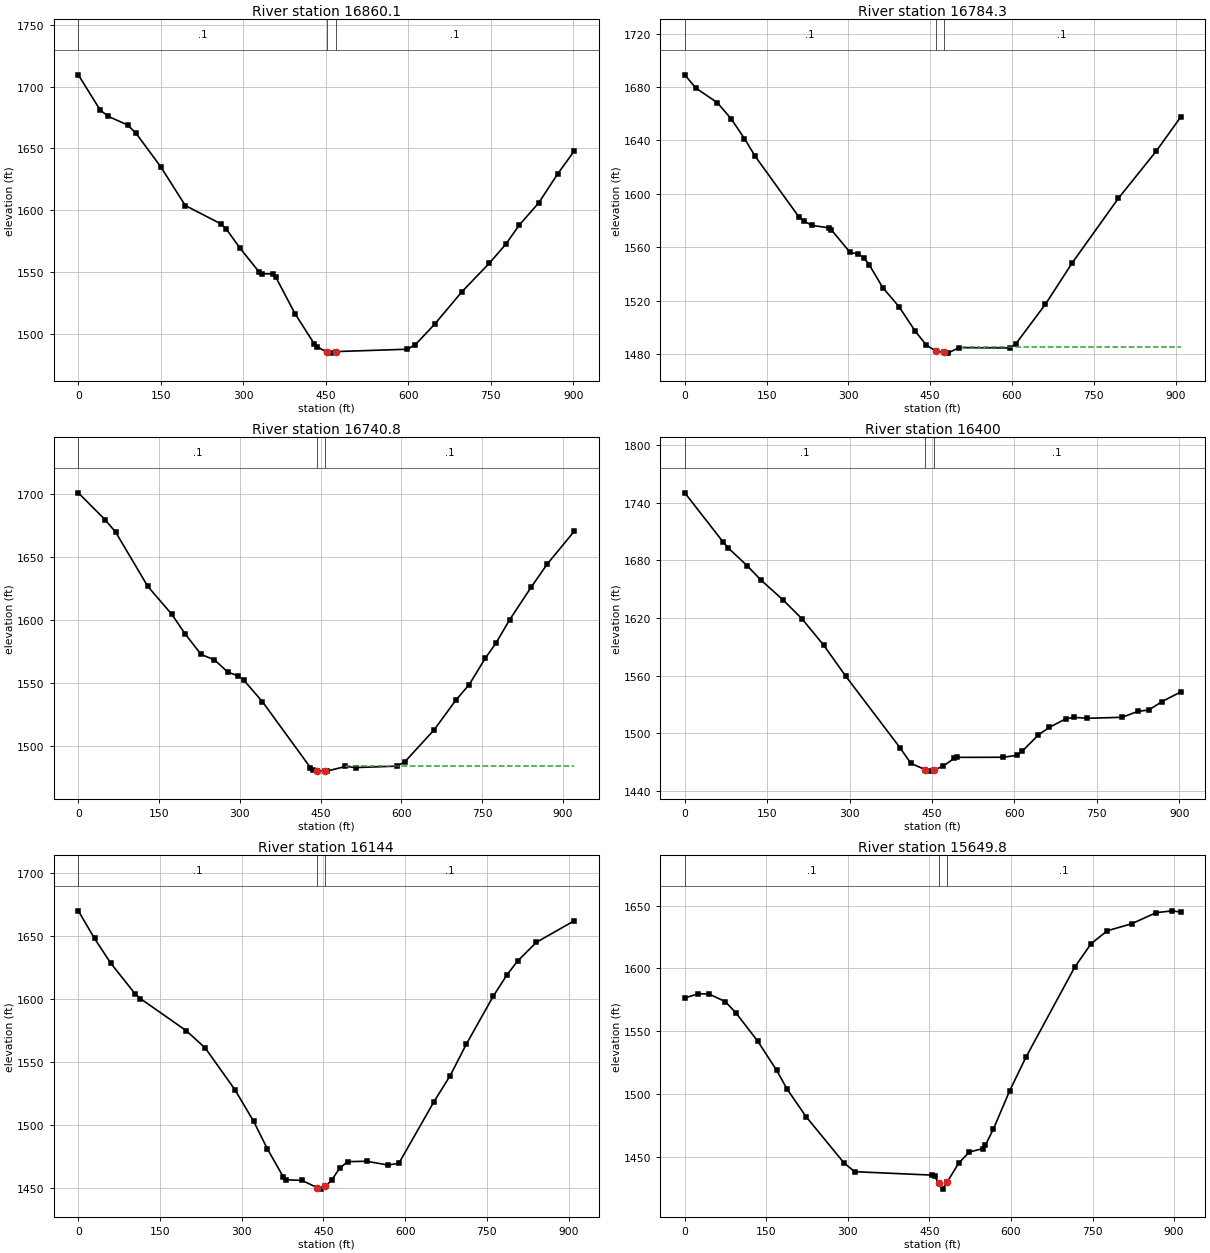
Type RM Length L Ch R = 1 ,16860.1 ,77.5,75.7,73.8
XS GIS Cut Line= 4
     1759308.467       250452.29     1758900.009      250565.446
     1758816.483      250597.779     1758475.643      250783.692
#Sta/Elev= 30
       0 1709.46    39.9 1680.85    54.8 1675.85    89.8 1668.86   104.7 1662.35
   149.6 1635.35   194.5 1603.87   259.3 1589.06   269.3 1584.74   294.2  1569.3
   329.1    1550   334.1 1548.77     354 1548.63     359  1546.1   393.9 1516.58
   428.8 1492.31   433.8 1489.86   452.7 1485.23   458.7 1484.63   467.7 1485.87
     598 1487.78     613  1491.5   647.8 1507.96   697.6 1534.28   747.4 1557.27
   777.2 1572.58   802.1 1588.26     837 1605.92   871.8 1629.56   901.6 1647.83
#Mann= 3 , 0 , 0
       0      .1       0   452.7    .045       0   467.7      .1       0
Bank Sta=452.7,467.7
XS Rating Curve= 0 ,0
Exp/Cntr=0.3,0.1

Type RM Length L Ch R = 1 ,16784.3 ,38.2,43.5,52
XS GIS Cut Line= 4
     1759279.245      250384.922     1758857.573      250501.454
     1758763.269      250547.259      1758419.06      250673.895
#Sta/Elev= 30
       0 1689.16    19.9 1679.34    59.7 1668.29    84.5 1656.44   109.4 1641.45
   129.2 1628.06   208.8 1582.97   218.7 1579.46   233.6 1576.34   263.5  1574.6
   268.4 1573.22   303.2 1556.08   318.2 1554.95   328.1 1552.24     338 1547.02
   362.9 1529.83   392.7 1515.53   422.6 1497.07   442.5 1486.88     460 1482.25
     475 1481.25   482.4  1480.7   502.4 1484.81   596.8 1484.59   606.8 1487.55
   661.3 1517.38   710.8 1548.57   795.1 1596.72   864.5 1632.07   909.1 1657.45
#Mann= 3 , 0 , 0
       0      .1       0     460    .045       0     475      .1       0
#XS Ineff= 2 ,-1
  508.51  541.65 1484.94  548.95   909.1 1485.17
Permanent Ineff=
       F       F
Bank Sta=460,475
XS Rating Curve= 0 ,0
Exp/Cntr=0.3,0.1

Type RM Length L Ch R = 1 ,16740.8 ,338,340.8,340.6
XS GIS Cut Line= 4
     1759255.457      250341.543     1758833.768       250471.15
     1758778.943      250475.411     1758366.852      250578.566
#Sta/Elev= 30
       0 1701.05    49.6 1679.77    69.4 1669.85   128.9 1626.95   173.5 1604.81
   198.3 1589.28     228 1572.94   252.8 1568.66   277.6 1558.96   297.4 1555.87
   307.3 1552.59     342 1535.45   431.2 1483.17   436.2 1481.12   443.2 1480.77
   458.2 1480.45   461.2 1480.44   496.2 1484.11   516.1 1483.28   591.1 1484.39
   606.1 1487.64   661.1 1513.27     701 1536.57     726 1549.01     756 1569.96
     776 1582.14     801 1600.31     841 1626.16     871  1644.6     921  1670.5
#Mann= 3 , 0 , 0
       0      .1       0   443.2    .045       0   458.2      .1       0
#XS Ineff= 2 , 0
                          496.39         1484.12
Permanent Ineff=
       F       F
Bank Sta=443.2,458.2
XS Rating Curve= 0 ,0
Exp/Cntr=0.3,0.1

Type RM Length L Ch R = 1 ,16400   ,255.5,256,256.6
XS GIS Cut Line= 5
     1759228.076      250113.587     1758846.471      250129.554
     1758738.378      250138.601     1758476.042      250188.631
     1758335.534      250225.354
#Sta/Elev= 30
       0 1750.15    69.4 1699.22    79.4 1692.66   114.1 1674.01   138.9 1659.24
   178.6 1638.91   213.3 1619.11     253 1591.56   292.6 1559.74   391.8    1485
   411.5 1468.74   438.2 1462.05     446 1460.64   453.2  1461.6   470.7 1465.94
   490.4 1473.98   495.4 1474.95   579.4 1475.07   604.2 1477.01     614  1481.2
   643.7 1498.23   663.5 1506.13   693.2 1514.91     708 1516.63   732.8 1515.62
   796.2 1516.63   825.2 1522.91   844.6 1524.16   868.8 1533.01   902.7 1542.97
#Mann= 3 , 0 , 0
       0      .1       0   438.2    .045       0   453.2      .1       0
Bank Sta=438.2,453.2
XS Rating Curve= 0 ,0
Exp/Cntr=0.3,0.1

Type RM Length L Ch R = 1 ,16144   ,493.6,494.2,494.9
XS GIS Cut Line= 4
     1759202.064      249830.167     1758838.487      249877.279
     1758705.963      249885.262     1758298.677      249939.671
#Sta/Elev= 30
       0 1670.27    29.7 1648.32    59.4 1628.75     104 1604.37     114 1600.48
   198.2 1574.95   232.8 1561.33   287.4 1528.11     322 1502.84   346.8 1481.22
   376.4 1458.66   381.4 1456.46   410.9 1455.94   438.5  1450.2   445.3 1449.03
   453.5  1451.2     465 1456.16   479.7 1465.65   494.5 1470.87   529.1  1471.2
   568.7 1468.18   588.5 1469.59   652.8 1518.46   682.6 1539.17   712.3 1564.25
   761.8 1602.41   786.5 1619.08   806.3 1630.27     841 1645.25   910.3 1662.32
#Mann= 3 , 0 , 0
       0      .1       0   438.5    .045       0   453.5      .1       0
Bank Sta=438.5,453.5
XS Rating Curve= 0 ,0
Exp/Cntr=0.3,0.1

Type RM Length L Ch R = 1 ,15649.8 ,306.9,300.6,294.3
XS GIS Cut Line= 4
     1759218.454      249342.176      1758865.28      249395.594
     1758684.924      249402.793       1758310.6      249410.058
#Sta/Elev= 30
       0 1576.47    24.8 1579.89    44.6 1579.65    74.4 1573.62    94.3 1564.51
     134 1542.22   168.7 1519.17   188.5 1503.82   223.2 1482.04   292.7 1445.42
   312.5 1438.37   454.8 1435.64   459.6 1434.58   467.3  1429.2   474.3  1424.5
   482.3 1429.86   503.5 1444.93   523.1 1453.95   547.7  1456.7   552.7 1459.23
   567.6 1472.18   597.6 1502.65   627.6 1529.42   717.4 1601.05   747.4 1619.68
   777.3 1629.93   822.2 1635.53   867.2 1644.34   897.1 1645.78   912.1 1644.77
#Mann= 3 , 0 , 0
       0      .1       0   467.3    .045       0   482.3      .1       0
Bank Sta=467.3,482.3
XS Rating Curve= 0 ,0
Exp/Cntr=0.3,0.1

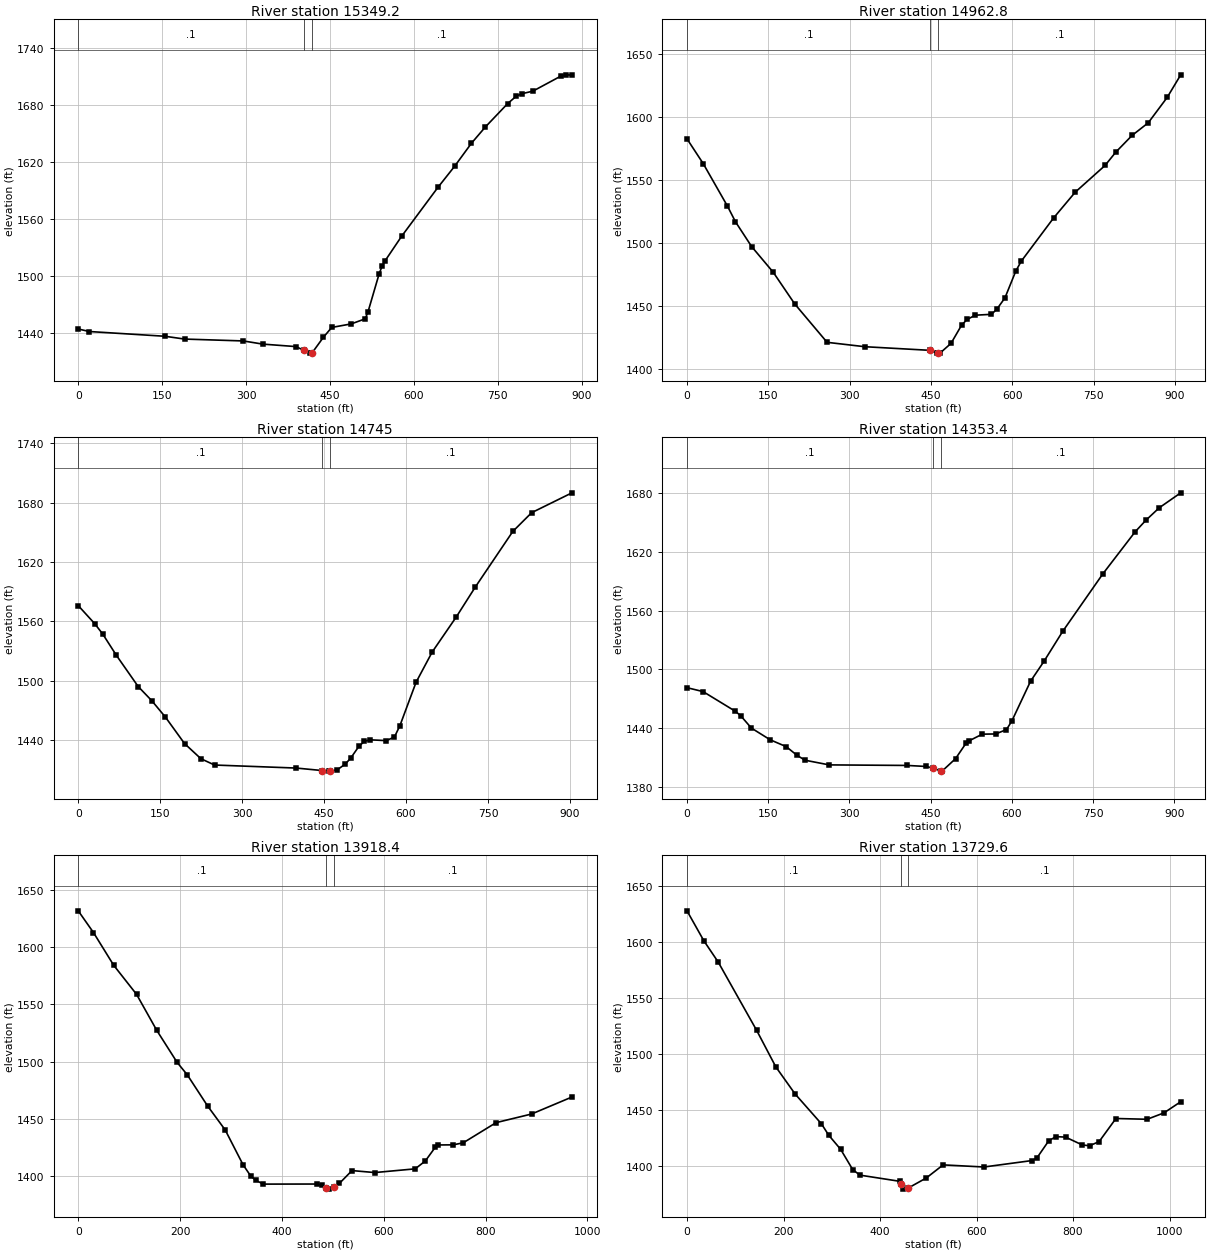
Type RM Length L Ch R = 1 ,15349.2 ,389.8,386.4,383.1
XS GIS Cut Line= 4
     1759118.777      248960.794     1758786.741      249086.233
      1758707.93      249112.504     1758298.214      249284.271
#Sta/Elev= 30
       0 1444.26      20  1441.6     155 1436.61     190 1433.66     295 1431.68
   329.9 1428.34   389.2 1425.73   403.4 1421.71   413.6 1418.85   418.4 1419.49
     438 1435.46     453  1445.9   487.9 1449.64   512.9 1454.99   517.9 1462.41
   537.8  1502.5   542.8 1510.19   547.8  1515.6   577.8 1541.84   642.7 1593.36
   672.6 1615.63   702.6 1639.84   727.5    1657   767.5 1681.73   782.4 1689.28
   792.4 1692.02   812.4 1694.75   862.3 1710.57   872.3 1711.96   882.3 1711.68
#Mann= 3 , 0 , 0
       0      .1       0   403.4    .045       0   418.4      .1       0
Bank Sta=403.4,418.4
XS Rating Curve= 0 ,0
Exp/Cntr=0.3,0.1

Type RM Length L Ch R = 1 ,14962.8 ,217.6,217.8,217.9
XS GIS Cut Line= 3
     1758974.603      248549.714     1758491.867      248794.867
     1758157.376      248950.549
#Sta/Elev= 30
       0 1582.47    29.8 1562.94    74.5 1529.27    89.4 1516.76   119.2 1497.12
     159 1476.79   198.7 1451.65   258.3 1421.27   327.8  1417.8   447.7 1414.93
   461.9 1412.71   462.7 1412.73   466.9 1412.87   486.8 1420.42   506.6 1435.07
   516.6 1439.38   531.5 1442.77   561.4 1443.45   571.3 1447.52   586.3  1456.5
   606.2 1477.66   616.2 1485.46     676 1519.82   715.9 1540.25   770.8 1561.37
   790.7 1571.97   820.6 1585.16   850.5  1595.2   885.4 1615.29   910.4 1633.21
#Mann= 3 , 0 , 0
       0      .1       0   447.7    .045       0   462.7      .1       0
Bank Sta=447.7,462.7
XS Rating Curve= 0 ,0
Exp/Cntr=0.3,0.1

Type RM Length L Ch R = 1 ,14745   ,391.2,391.6,392
XS GIS Cut Line= 4
     1758870.812      248358.442     1758519.543       248537.27
       1758332.2      248630.942       1758059.7      248756.547
#Sta/Elev= 30
       0 1575.83    29.9 1557.72    44.9 1547.04    69.8 1525.55   109.8 1493.93
   134.7  1479.6   159.7 1462.97   194.6 1436.28   224.5 1420.98   249.5 1414.58
   399.2 1411.51   446.7 1408.99     459 1408.41   461.7 1408.42     474 1409.69
   488.9  1415.6   498.9 1421.71   513.9  1433.6   523.8  1438.5   533.8  1440.1
   563.7 1439.27   578.7 1442.85   588.7 1454.26   618.4 1498.33   647.9  1528.9
   692.2 1564.55   726.6 1594.44   795.5 1650.88   829.9  1669.8   903.7 1689.89
#Mann= 3 , 0 , 0
       0      .1       0   446.7    .045       0   461.7      .1       0
Bank Sta=446.7,461.7
XS Rating Curve= 0 ,0
Exp/Cntr=0.3,0.1

Type RM Length L Ch R = 1 ,14353.4 ,423.8,435.1,446.3
XS GIS Cut Line= 4
     1758705.557       248050.46     1758362.698      248180.407
     1758246.215      248236.117     1757865.607      248403.879
#Sta/Elev= 30
       0 1481.37    29.7 1477.36    89.2 1457.27    99.1 1452.73   118.9 1440.08
   153.6 1428.11   183.3 1421.08   203.2 1412.21     218 1407.22   262.6 1402.45
   406.4 1401.89   441.2 1400.86     454 1399.29     469 1396.09     471 1396.08
   495.8 1408.78   515.6 1424.89   520.5 1426.92   545.3 1433.86     570 1434.08
   589.9 1438.53   599.8 1447.25   634.4 1487.97   659.2  1508.3   693.8 1538.96
   768.1 1597.84   827.5 1640.65   847.4 1652.48   872.1 1665.25   911.7  1680.5
#Mann= 3 , 0 , 0
       0      .1       0     454    .045       0     469      .1       0
Bank Sta=454,469
XS Rating Curve= 0 ,0
Exp/Cntr=0.3,0.1

Type RM Length L Ch R = 1 ,13918.4 ,189.7,188.7,187.8
XS GIS Cut Line= 4
     1758696.051      247654.117     1758415.371      247824.898
     1758191.811      247811.617     1757824.265      248008.579
#Sta/Elev= 30
       0 1631.92    29.9 1612.93    69.7 1584.25   114.5 1558.87   154.3 1527.26
   194.2 1499.31   214.1 1488.44   253.9 1461.26   288.7 1440.12   323.6 1409.79
   338.5 1400.02   348.5 1396.17   363.4  1392.8   467.9 1392.87   477.9 1391.89
   486.7 1389.42   492.8 1388.41   501.7 1389.96   512.7 1393.38   537.6 1404.64
   582.3 1402.91   661.7 1406.16   681.6 1413.07   701.4 1425.23   706.4 1427.05
   736.2 1427.16     756 1428.94   820.6 1446.61   890.1 1454.12   969.5 1469.01
#Mann= 3 , 0 , 0
       0      .1       0   486.7    .045       0   501.7      .1       0
Bank Sta=486.7,501.7
XS Rating Curve= 0 ,0
Exp/Cntr=0.3,0.1

Type RM Length L Ch R = 1 ,13729.6 ,156.7,143.8,132.1
XS GIS Cut Line= 4
     1758684.271      247485.017     1758342.124      247634.197
     1758219.389      247634.197      1757821.66      247980.285
#Sta/Elev= 30
       0 1627.43    34.8 1600.78    64.7 1581.66   144.3 1520.73   184.1 1488.07
     224 1463.91   278.7  1437.2   293.6 1427.13   318.5 1414.42   343.4 1396.39
   358.3 1391.43     442 1385.84   443.7 1383.44   446.9 1378.93   458.7 1379.96
     496 1388.91   530.8 1400.58   615.4 1398.69   714.8 1404.43   724.8 1406.56
   749.6 1422.03   764.6 1425.81   784.5 1425.37   819.3 1418.36   834.2 1417.66
   854.1 1421.38   888.9 1441.99   953.6  1441.3   988.4    1447  1023.2 1456.97
#Mann= 3 , 0 , 0
       0      .1       0   443.7    .045       0   458.7      .1       0
Bank Sta=443.7,458.7
XS Rating Curve= 0 ,0
Exp/Cntr=0.3,0.1

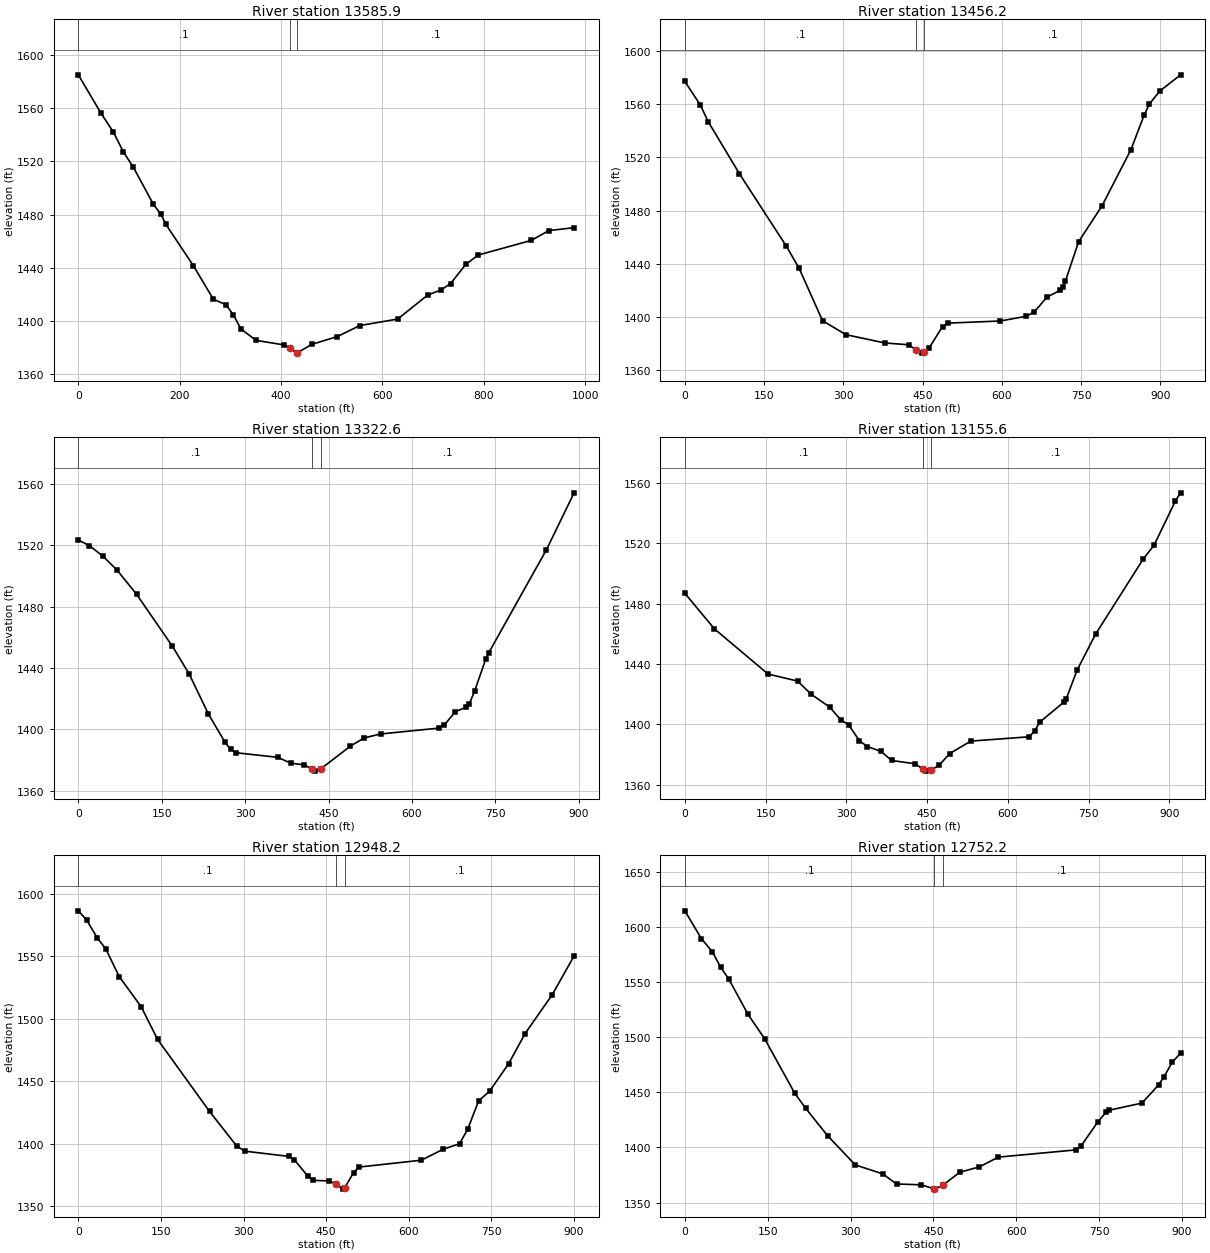
Type RM Length L Ch R = 1 ,13585.9 ,136.1,129.6,123.1
XS GIS Cut Line= 4
     1758597.899      247356.096       1758292.8      247455.256
     1758131.648      247545.899     1757760.343      247837.695
#Sta/Elev= 30
       0 1585.28    44.4 1556.58    69.1 1542.16    88.8 1527.29   108.6 1515.61
   148.1 1487.72   162.9 1480.27   172.7 1472.62     227 1441.46   266.5 1416.17
   291.2 1412.12     306 1404.31   320.8  1393.8   350.8 1385.22   405.8 1381.82
   417.3 1379.15   430.8 1375.62   432.3  1375.9   460.7 1382.22   510.7 1388.07
   555.4  1396.4     630 1401.28   689.6 1419.49   714.5 1423.01   734.4 1428.02
   764.2 1442.45     789 1449.54   893.4 1460.52   928.2 1467.93     978 1470.14
#Mann= 3 , 0 , 0
       0      .1       0   417.3    .045       0   432.3      .1       0
Bank Sta=417.3,432.3
XS Rating Curve= 0 ,0
Exp/Cntr=0.3,0.1

Type RM Length L Ch R = 1 ,13456.2 ,131.5,133.6,135.8
XS GIS Cut Line= 4
     1758506.046      247208.645     1758229.712      247296.962
     1758096.965      247429.709     1757709.231       247678.68
#Sta/Elev= 30
       0 1577.08    29.5 1559.18    44.2 1546.84   103.3 1507.63   191.8  1453.4
   216.4 1436.51   260.6 1397.19   304.9 1386.65     379  1380.4   423.5 1379.07
   438.2 1374.98   448.2 1372.78   453.2 1373.37     463 1376.99   487.8  1392.8
   497.7 1395.35   596.8 1396.93   646.3 1400.48   661.2 1403.62   685.9    1415
   710.7 1420.05   715.7  1422.2   720.6 1427.05   745.4 1456.51     790 1483.72
   844.5 1525.76   869.3 1551.56   879.2 1559.94     899 1569.82   938.6 1582.05
#Mann= 3 , 0 , 0
       0      .1       0   438.2    .045       0   453.2      .1       0
Bank Sta=438.2,453.2
XS Rating Curve= 0 ,0
Exp/Cntr=0.3,0.1

Type RM Length L Ch R = 1 ,13322.6 ,167.2,167.1,166.8
XS GIS Cut Line= 4
     1758403.074      247052.022     1758110.897      247242.102
     1758033.734       247307.34     1757656.226      247536.702
#Sta/Elev= 30
       0 1523.53    19.9 1519.83    44.8 1512.75    69.7 1503.84   104.6 1488.17
   169.3 1454.14   199.2 1436.22     234 1409.95   263.9 1391.57   273.9 1386.98
   283.8  1384.8   358.2 1381.84   382.2 1377.99   406.3 1376.95   420.6 1373.94
   425.6 1372.83   435.6 1374.21   489.3 1389.18   514.1  1394.5   543.9 1397.07
   648.1 1400.87   658.1 1402.95   677.9 1411.62   697.8 1414.59   702.7 1416.39
   712.7 1425.27   732.5 1445.88   737.5 1449.74   841.7 1517.22   891.3 1554.25
#Mann= 3 , 0 , 0
       0      .1       0   420.6    .045       0   435.6      .1       0
Bank Sta=420.6,435.6
XS Rating Curve= 0 ,0
Exp/Cntr=0.3,0.1

Type RM Length L Ch R = 1 ,13155.6 ,201.3,207.4,213.4
XS GIS Cut Line= 4
     1758313.753      246908.884     1757994.565      247122.609
     1757864.183      247234.191     1757518.662      247352.349
#Sta/Elev= 30
       0 1486.79    54.9 1463.26   154.6 1433.33   209.5 1428.69   234.5    1420
   269.4 1411.35   289.4  1403.1   304.3  1399.7   324.3 1389.13   339.2 1385.31
   364.2 1382.13   384.1  1376.1   428.3 1373.91   441.6 1370.42   447.9 1369.06
   456.6 1369.62   472.4 1372.97     492 1380.72   531.2 1388.94   639.6  1391.8
   649.5 1395.57   659.4 1401.58   703.8 1414.67   708.7 1417.13   728.5 1435.89
     763 1459.81   851.8  1509.7   871.6 1518.68     911 1547.83   920.9 1553.34
#Mann= 3 , 0 , 0
       0      .1       0   441.6    .045       0   456.6      .1       0
Bank Sta=441.6,456.6
XS Rating Curve= 0 ,0
Exp/Cntr=0.3,0.1

Type RM Length L Ch R = 1 ,12948.2 ,192.3,196,199.7
XS GIS Cut Line= 4
      1758261.83      246758.992     1757909.683      246952.844
      1757754.83      247026.256     1757454.301      247154.727
#Sta/Elev= 30
       0 1586.58    14.9 1579.36    34.7 1564.65    49.6 1556.24    74.4 1533.77
   114.1 1509.72   143.9  1483.5   238.2 1425.78   287.8 1397.88   302.7 1393.89
   382.1 1389.72     392 1387.14   416.7 1373.89   426.5 1370.49   455.8 1370.04
   468.4 1367.23   480.3 1363.47   483.4 1364.34   499.9 1376.77   509.7 1381.17
   622.9 1386.65   662.5 1395.47   692.2  1399.8   707.1 1411.62   726.9 1434.29
   746.7 1441.95   781.3 1463.96     811 1488.03   860.6 1519.38   900.2 1550.44
#Mann= 3 , 0 , 0
       0      .1       0   468.4    .045       0   483.4      .1       0
Bank Sta=468.4,483.4
XS Rating Curve= 0 ,0
Exp/Cntr=0.3,0.1

Type RM Length L Ch R = 1 ,12752.2 ,106.6,105.9,105.1
XS GIS Cut Line= 4
     1758231.418      246672.162     1757857.707      246776.843
     1757733.255      246812.669      1757380.39      246953.176
#Sta/Elev= 30
       0 1614.48    29.8 1589.31    49.8 1577.36    64.7 1563.44    79.6 1552.53
   114.4 1520.51   144.3 1498.56     199 1448.98   218.9 1435.26   258.7 1410.37
   308.5 1384.11   358.2 1375.97   383.1 1366.82   427.9 1366.05   451.8 1362.33
   452.8 1362.15   466.8 1365.63   497.7 1377.47   532.6 1382.22   567.6 1391.18
   707.5 1397.71   717.5 1401.54   747.5 1423.07   762.5 1431.98   767.5 1433.64
   827.4 1440.16   857.4  1456.6   867.4 1464.02   882.4 1477.42   897.4 1485.36
#Mann= 3 , 0 , 0
       0      .1       0   451.8    .045       0   466.8      .1       0
Bank Sta=451.8,466.8
XS Rating Curve= 0 ,0
Exp/Cntr=0.3,0.1

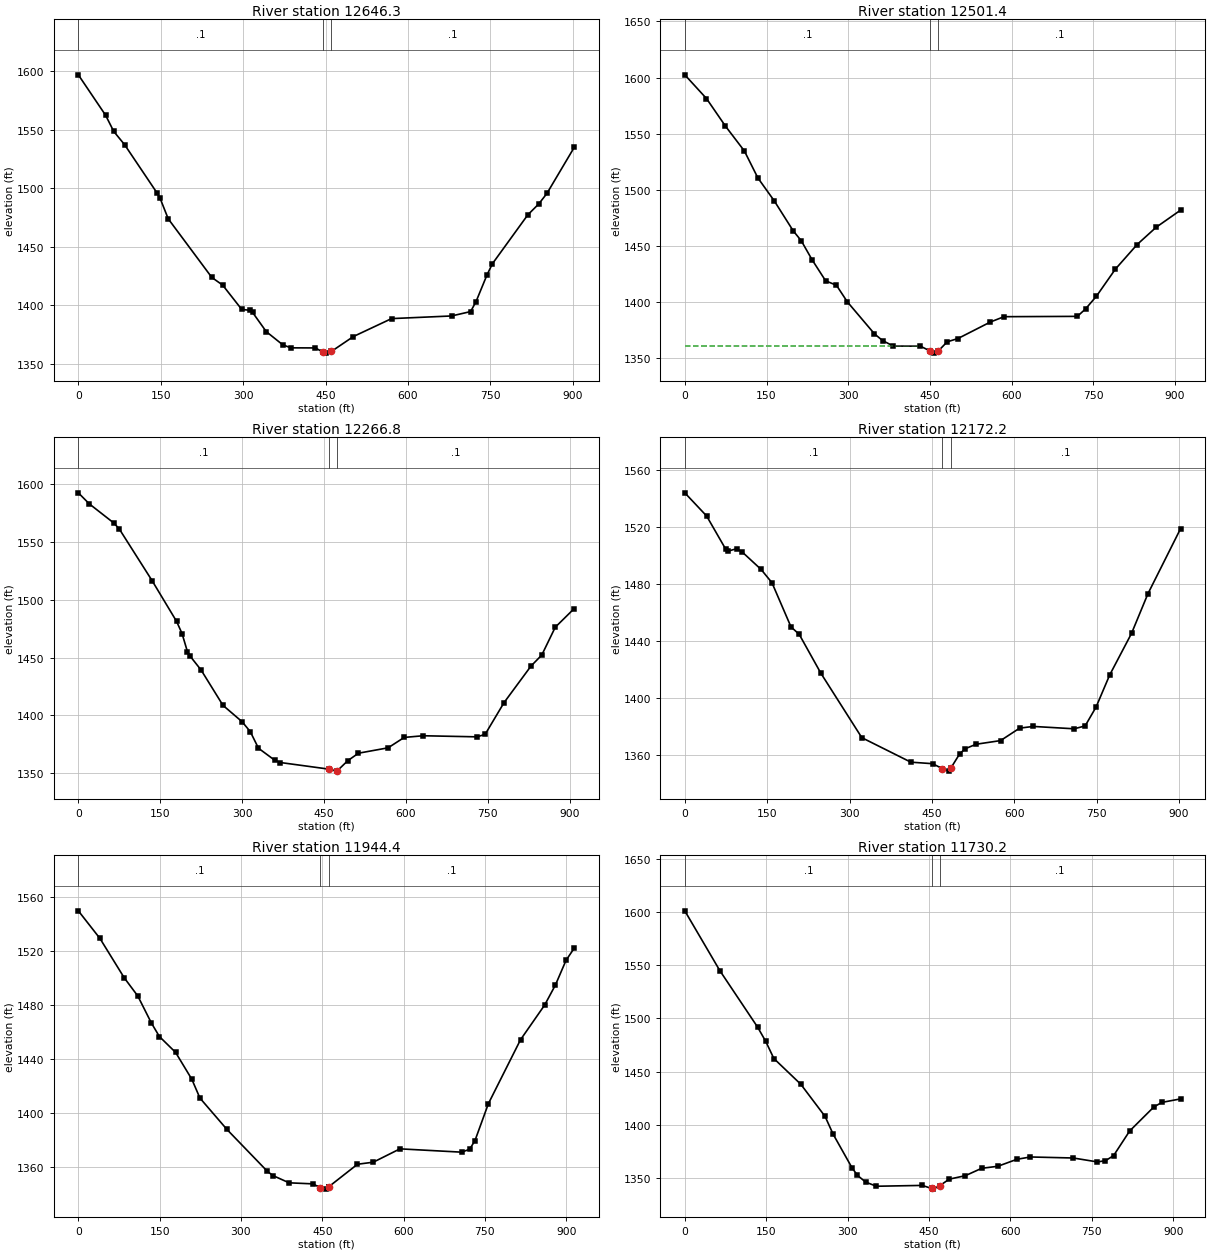
Type RM Length L Ch R = 1 ,12646.3 ,145.1,145,144.8
XS GIS Cut Line= 4
     1758200.972       246577.55     1757807.469      246679.861
     1757713.178      246710.385     1757327.395      246803.814
#Sta/Elev= 30
       0 1597.05    49.6 1562.54    64.5  1548.7    84.3 1537.33   143.8 1495.77
   148.8 1491.63   163.6 1474.06     243 1423.96   262.8 1417.38   297.5  1396.6
   312.4 1395.91   317.3 1394.01   342.1 1377.68   371.9 1366.49   386.8 1363.81
   431.4 1363.74   445.5 1360.14   451.2  1359.3   460.5  1360.7   500.7 1373.47
   570.2 1388.79   679.4 1391.05   714.1 1394.79     724 1403.34   743.9 1426.07
   753.8 1435.68   818.3 1477.47   838.1 1486.74     853 1495.71   902.6 1534.98
#Mann= 3 , 0 , 0
       0      .1       0   445.5    .045       0   460.5      .1       0
Bank Sta=445.5,460.5
XS Rating Curve= 0 ,0
Exp/Cntr=0.3,0.1

Type RM Length L Ch R = 1 ,12501.4 ,237.2,234.5,231.9
XS GIS Cut Line= 4
     1758159.318      246426.781     1757762.917      246541.535
     1757664.786      246574.244     1757285.208      246679.828
#Sta/Elev= 30
       0 1602.45    39.8 1581.35    74.6 1556.79   109.4 1534.63   134.2 1510.61
   164.1 1490.33   198.9 1463.63   213.8  1454.7   233.7 1437.75   258.5 1419.06
   278.4 1415.08   298.3 1400.36     348 1371.91     363 1365.85   382.8 1360.98
   432.4 1360.86   450.5 1356.57     457 1354.68   465.5 1356.69   481.6 1364.74
   501.3 1367.66     561  1382.4   585.9 1387.12   720.6 1387.41   735.6 1394.04
   755.5 1405.31   790.4  1429.5   830.3 1451.39   865.2 1466.73   910.1    1482
#Mann= 3 , 0 , 0
       0      .1       0   450.5    .045       0   465.5      .1       0
#XS Ineff= 2 , 0
          432.04 1360.87
Permanent Ineff=
       F       F
Bank Sta=450.5,465.5
XS Rating Curve= 0 ,0
Exp/Cntr=0.3,0.1

Type RM Length L Ch R = 1 ,12266.8 ,90.9,94.7,98.5
XS GIS Cut Line= 4
     1758100.629      246245.039     1757714.996      246302.097
     1757514.309      246396.538     1757236.889      246500.817
#Sta/Elev= 30
       0 1592.46      20 1582.95      65 1566.35      75  1561.2   134.9 1516.64
   179.9 1481.31   189.9 1470.79   199.9 1454.96   204.9 1451.12   224.9 1439.18
   264.9 1408.67   299.9 1394.52   314.9 1385.94   329.9 1371.59   359.8 1361.17
   369.8 1359.25   458.6 1353.54   473.6  1351.8   493.3 1360.79     513  1367.3
   567.3 1371.96   596.8 1380.95   631.4 1382.39   730.2 1381.45     745 1383.62
   779.6 1411.05     829 1442.68   848.7 1452.19   873.4 1476.24     908 1492.32
#Mann= 3 , 0 , 0
       0      .1       0   458.6    .045       0   473.6      .1       0
Bank Sta=458.6,473.6
XS Rating Curve= 0 ,0
Exp/Cntr=0.3,0.1

Type RM Length L Ch R = 1 ,12172.2 ,223.7,227.8,231.9
XS GIS Cut Line= 4
     1758073.084      246178.144      1757679.58      246229.299
     1757488.731      246282.422     1757193.604       246370.96
#Sta/Elev= 30
       0 1544.09    39.7 1527.85    74.4 1504.61    79.4 1503.26    94.2 1504.82
   104.2 1502.68   138.9 1490.34   158.7 1481.02   193.4    1450   208.3  1444.8
     248 1417.35   322.4 1372.24   411.7 1355.05   451.3 1353.98   469.2 1350.48
     481 1348.76   484.2 1350.69   500.8    1361   510.7 1364.48   530.5 1367.63
   575.1 1370.19   609.8 1378.93   634.7 1380.13   709.2 1378.47   729.1  1380.5
     749 1393.72   773.8 1416.24   813.6 1445.44   843.4 1473.22     903 1519.02
#Mann= 3 , 0 , 0
       0      .1       0   469.2    .045       0   484.2      .1       0
Bank Sta=469.2,484.2
XS Rating Curve= 0 ,0
Exp/Cntr=0.3,0.1

Type RM Length L Ch R = 1 ,11944.4 ,212.1,214.1,216.1
XS GIS Cut Line= 4
     1758006.128      245967.733     1757621.174      246022.318
      1757461.82      246036.685     1757104.927      246116.699
#Sta/Elev= 30
       0 1549.45    39.9 1529.04    84.7 1499.98   109.7 1486.56   134.6 1466.74
   149.5 1456.65   179.4 1444.92   209.4 1425.05   224.3  1411.2   274.2    1388
   348.9 1357.03   358.9 1353.99   388.8 1348.63   432.4 1347.86   446.5 1345.06
   456.7 1343.97   461.5 1345.57   461.5 1345.58   514.9 1362.34     544 1363.85
   593.3 1373.71     707 1371.26   721.8 1373.39   731.7 1379.87   756.4 1407.08
   815.7  1454.3   860.2  1479.9     880 1494.65   899.7 1512.97   914.6  1521.8
#Mann= 3 , 0 , 0
       0      .1       0   446.5    .045       0   461.5      .1       0
Bank Sta=446.5,461.5
XS Rating Curve= 0 ,0
Exp/Cntr=0.3,0.1

Type RM Length L Ch R = 1 ,11730.2 ,301,300.9,300.8
XS GIS Cut Line= 5
     1758022.253        245837.1     1757634.804      245820.593
       1757505.6      245819.964     1757424.013      245886.013
     1757132.406      245877.856
#Sta/Elev= 30
       0 1601.28    64.6 1544.95   134.2 1491.76   149.2 1478.31   164.1 1462.25
   213.8 1437.98   258.5 1407.71   273.4 1390.94   308.2 1359.31   318.2 1352.22
   333.1 1345.96     353 1341.98   437.5 1342.77     455  1339.9   457.4 1339.27
     470 1342.55   487.2 1348.65     517 1351.93     547 1358.86     577  1360.8
     612 1367.35   636.8 1369.54   715.9 1368.58   760.4 1364.88   775.2 1366.05
   790.1 1370.77   819.8 1394.02   864.2 1416.55   879.1 1420.92   913.7 1424.23
#Mann= 3 , 0 , 0
       0      .1       0     455    .045       0     470      .1       0
Bank Sta=455,470
XS Rating Curve= 0 ,0
Exp/Cntr=0.3,0.1