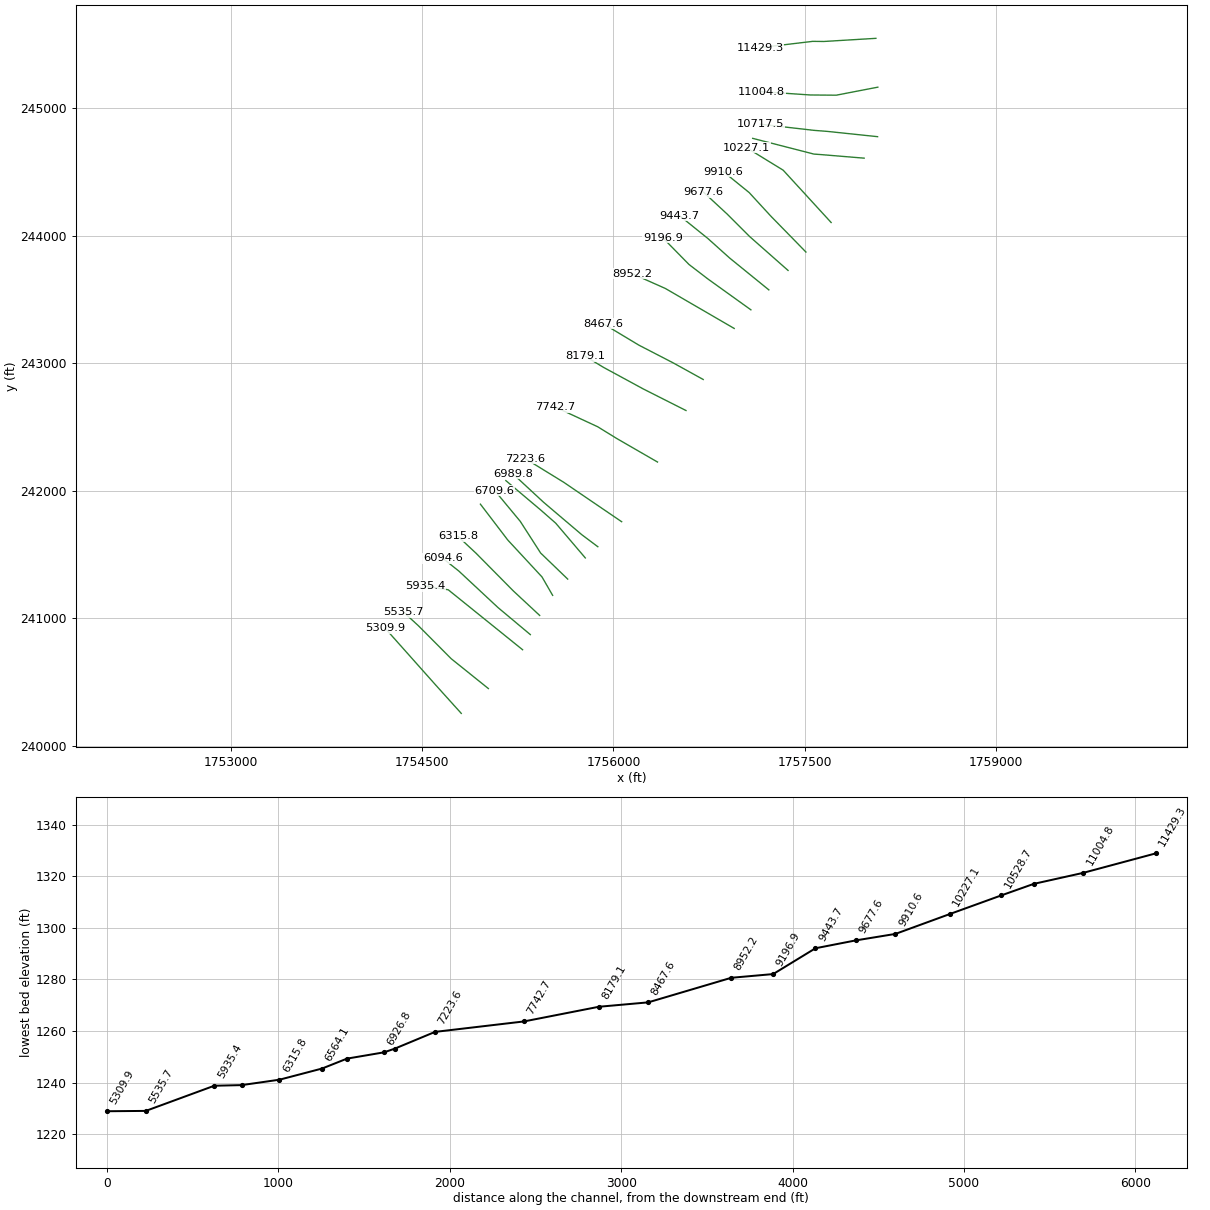
HEC-RAS study BigCubCr.prj: BigCubCr

--- BigCubCr.g01 (geometry) --- (continued)

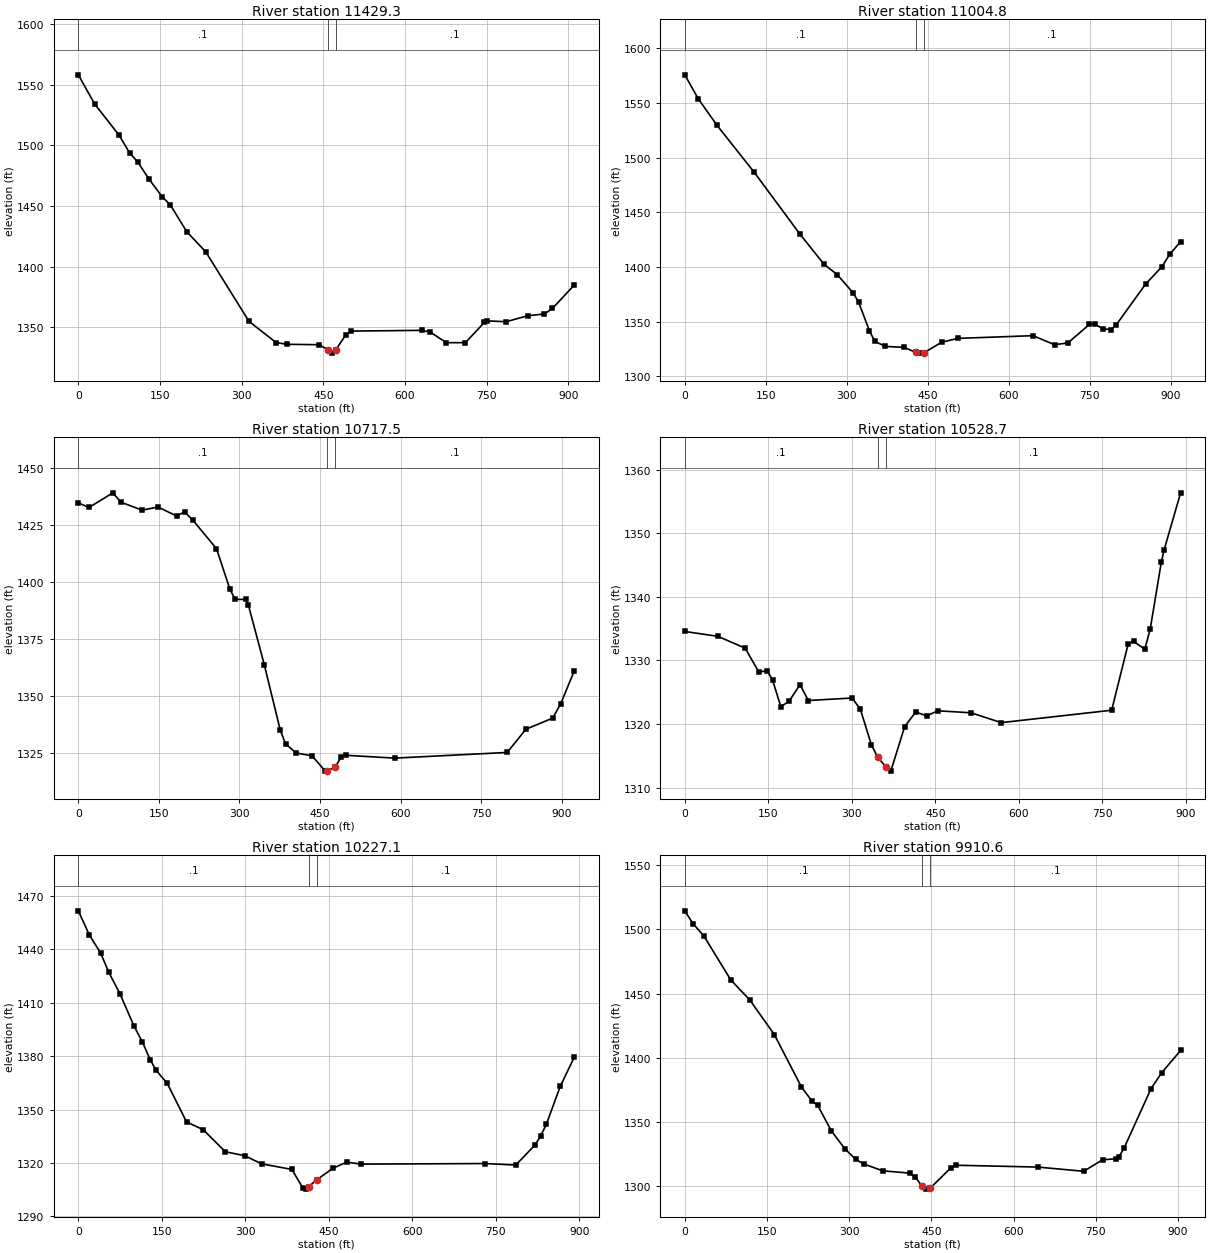
Type RM Length L Ch R = 1 ,11429.3 ,424.4,424.5,424.6
XS GIS Cut Line= 4
     1758057.501      245548.254     1757650.374      245523.672
     1757561.908      245524.489     1757150.417      245475.462
#Sta/Elev= 30
       0 1558.24    29.8  1534.3    74.6 1508.63    94.5 1493.66   109.4 1486.31
   129.3 1472.55   154.2 1457.67   169.1 1450.94     199 1428.99   233.8 1412.45
   313.4 1355.06   363.1  1337.6     383 1336.12   442.3 1335.79   458.2 1331.63
   466.8 1328.85   473.2 1331.71   491.4 1344.04   501.3 1347.01   631.1 1347.63
   646.1 1346.28   676.1 1337.47     711 1337.48     746  1354.3     751 1355.44
   785.9 1354.73   825.9 1359.73   855.8  1361.1   870.8 1365.67   910.7 1384.88
#Mann= 3 , 0 , 0
       0      .1       0   458.2    .045       0   473.2      .1       0
Bank Sta=458.2,473.2
XS Rating Curve= 0 ,0
Exp/Cntr=0.3,0.1

Type RM Length L Ch R = 1 ,11004.8 ,288.7,287.3,285.9
XS GIS Cut Line= 4
     1758072.598      245165.373     1757746.654      245102.491
     1757542.982      245104.204     1757161.074      245130.034
#Sta/Elev= 30
       0 1575.67    24.8 1553.88    59.4 1529.69   128.8 1486.45     213 1430.23
   257.6 1402.64   282.4 1393.01   312.1 1376.22     322 1367.73   341.9  1341.9
   351.8    1332   371.7 1327.41   406.5 1326.55   427.8 1321.92   436.3 1321.29
   442.8 1321.61     476 1331.28   505.8 1334.77     645 1337.24   684.8    1329
   709.6 1330.58   749.4 1347.55   759.3 1347.93   774.2 1343.64   789.2 1342.76
   799.1 1347.11   853.8 1384.56   883.6 1400.19   898.5 1411.78   918.4 1423.15
#Mann= 3 , 0 , 0
       0      .1       0   427.8    .045       0   442.8      .1       0
Bank Sta=427.8,442.8
XS Rating Curve= 0 ,0
Exp/Cntr=0.3,0.1

Type RM Length L Ch R = 1 ,10717.5 ,188.7,188.8,188.8
XS GIS Cut Line= 4
     1758070.816      244777.255     1757677.188      244818.587
     1757573.953      244826.616     1757152.645      244874.902
#Sta/Elev= 30
       0 1434.64    19.8 1432.61    64.3 1439.04    79.2 1434.92   118.7 1431.47
   148.4  1432.8     183  1428.9   197.9 1430.65   212.7 1427.21   257.3 1414.58
     282 1396.97   291.9 1392.34   311.7  1392.3   316.6 1389.95   346.3  1363.7
     376 1335.08   385.9    1329   405.6 1324.98   435.2 1323.78   459.9 1317.04
   463.4 1317.16   478.4 1318.81   489.5 1323.24   499.3 1323.97   589.1 1322.74
   798.7 1325.23   833.6 1335.41   883.5 1340.28   898.5 1346.66   923.4 1360.88
#Mann= 3 , 0 , 0
       0      .1       0   463.4    .045       0   478.4      .1       0
Bank Sta=463.4,478.4
XS Rating Curve= 0 ,0
Exp/Cntr=0.3,0.1

Type RM Length L Ch R = 1 ,10528.7 ,318.8,301.6,284.5
XS GIS Cut Line= 4
     1757965.502      244608.764     1757636.418       244636.03
     1757571.816      244640.748     1757091.641      244764.032
#Sta/Elev= 30
       0 1334.56    59.1  1333.8   108.4 1331.94   133.1 1328.17   147.9  1328.4
   157.7 1326.91   172.5 1322.73   187.3 1323.58     207  1326.2   221.8  1323.7
   300.6 1324.09   315.4 1322.31   335.2 1316.73   346.5 1314.78   361.5 1313.22
   370.1 1312.59     395  1319.6   414.8 1321.89   434.6 1321.29   454.5 1322.08
     514 1321.77   568.5 1320.22   766.8 1322.17   796.5  1332.6   806.5    1333
   826.3 1331.76   836.2    1335     856 1345.46     861 1347.39   890.7 1356.37
#Mann= 3 , 0 , 0
       0      .1       0   346.5    .045       0   361.5      .1       0
Bank Sta=346.5,361.5
XS Rating Curve= 0 ,0
Exp/Cntr=0.3,0.1

Type RM Length L Ch R = 1 ,10227.1 ,316.5,316.5,316.5
XS GIS Cut Line= 4
     1757706.752       244104.16     1757481.111      244350.485
     1757330.719      244514.376     1757045.798       244689.29
#Sta/Elev= 30
       0 1461.67    19.9 1448.02    39.9 1438.07    54.8 1427.08    74.8 1415.05
    99.7 1397.16   114.7 1388.24   129.6 1377.76   139.6 1372.11   159.6 1364.85
   194.4 1343.11   224.4 1338.71   264.2 1326.33   299.2 1324.09   329.1 1319.56
   383.5 1316.41   403.2 1306.15   408.2 1305.34     414 1306.78     429 1310.72
   457.6  1317.1   482.3 1320.51   507.1 1319.39   731.1 1319.71     786 1318.87
     821 1330.34   830.9 1335.41   840.9 1341.81   865.9 1363.15   890.8 1379.33
#Mann= 3 , 0 , 0
       0      .1       0     414    .045       0     429      .1       0
Bank Sta=414,429
XS Rating Curve= 0 ,0
Exp/Cntr=0.3,0.1

Type RM Length L Ch R = 1 ,9910.6  ,232,233,234
XS GIS Cut Line= 4
     1757509.041      243872.716     1757232.283      244155.859
       1757064.1      244338.945     1756861.855       244502.87
#Sta/Elev= 30
       0 1514.54    14.8 1504.62    34.6 1495.08    84.1 1460.59   118.8 1444.99
   163.3 1418.16   212.8 1377.33   232.6 1365.97   242.5    1363   267.3 1343.13
     292 1329.14   311.8 1320.88   326.6 1317.25   361.3 1311.92   410.8 1310.14
   420.8 1306.99   432.7 1300.14   440.7 1297.66   447.7 1298.37   485.4 1314.15
   495.4 1316.27   644.5 1314.85     728 1311.56   762.4 1320.51     787 1321.36
   791.9 1322.55   801.7 1329.62   850.8  1375.9   870.5 1388.43   904.9 1405.74
#Mann= 3 , 0 , 0
       0      .1       0   432.7    .045       0   447.7      .1       0
Bank Sta=432.7,447.7
XS Rating Curve= 0 ,0
Exp/Cntr=0.3,0.1

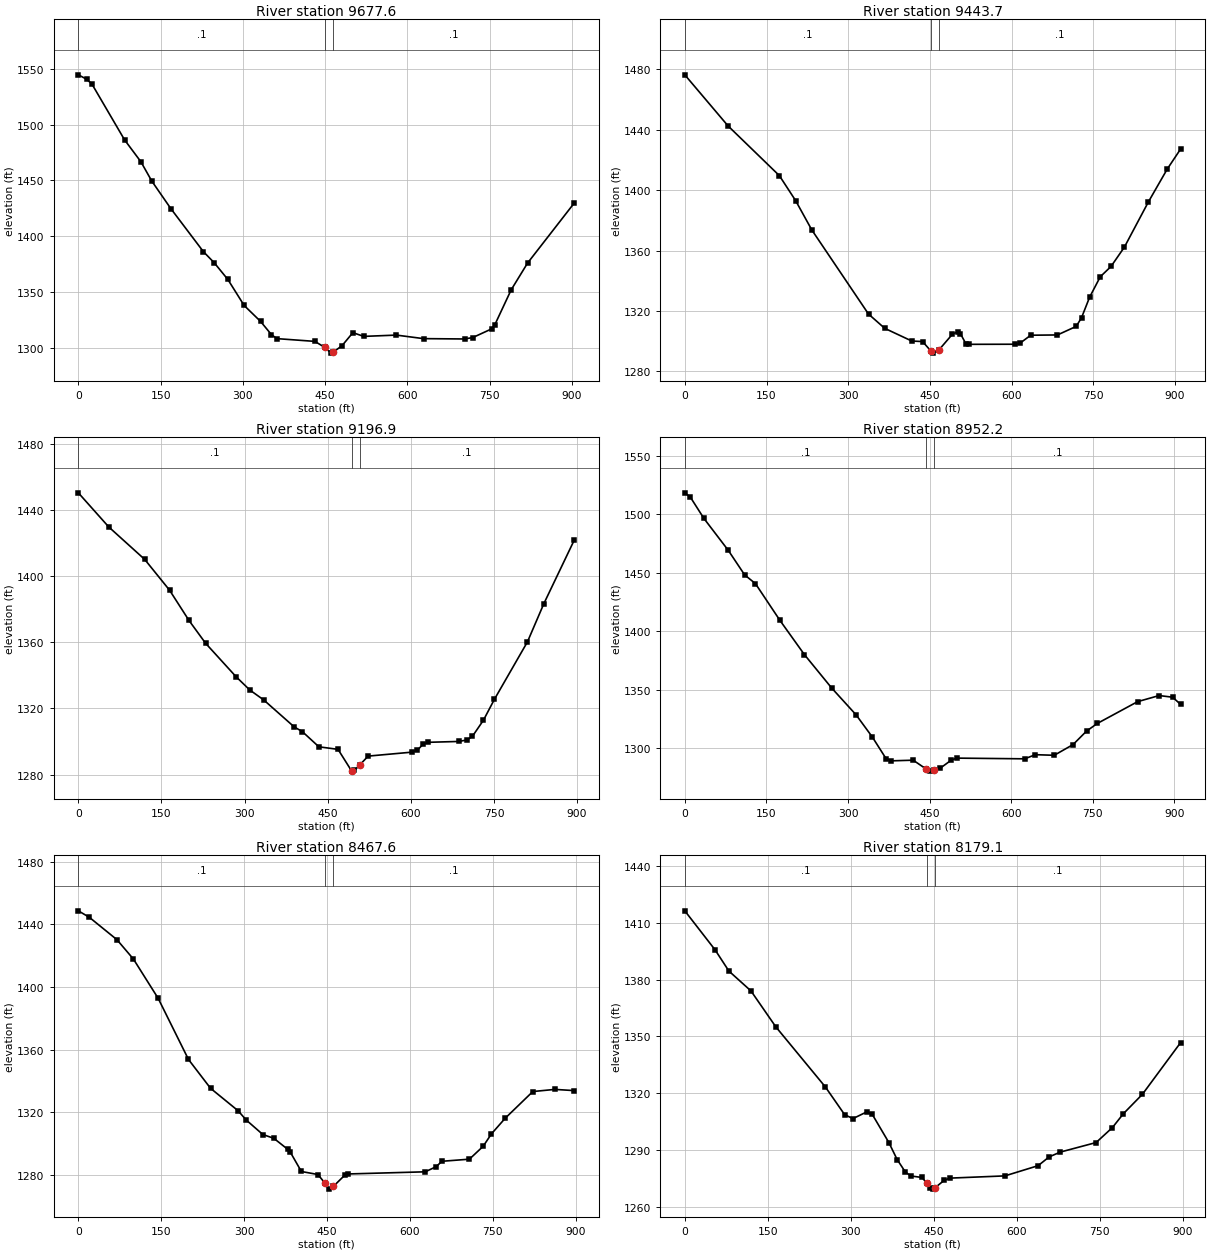
Type RM Length L Ch R = 1 ,9677.6  ,232.6,233.8,235.1
XS GIS Cut Line= 4
     1757368.713      243728.584     1757067.683      243994.199
     1756892.573      244169.308     1756705.659       244342.45
#Sta/Elev= 30
       0 1544.69    14.9 1540.82    24.8 1536.41    84.3 1486.36     114 1466.78
   133.8  1449.5   168.5 1424.82     228 1386.11   247.8 1376.13   272.6 1361.16
   302.3 1337.86   332.1 1323.62   351.9 1311.81   361.8 1308.14   431.2 1305.66
   448.8 1300.42   460.9 1295.13   463.8  1295.7   480.7 1301.79   500.5 1313.49
   520.3 1310.14   579.8  1311.3   629.3 1308.13   704.1 1307.82     719 1309.09
     754 1316.99     759 1320.27     789 1351.82     819 1375.92   903.9 1429.63
#Mann= 3 , 0 , 0
       0      .1       0   448.8    .045       0   463.8      .1       0
Bank Sta=448.8,463.8
XS Rating Curve= 0 ,0
Exp/Cntr=0.3,0.1

Type RM Length L Ch R = 1 ,9443.7  ,245.1,246.8,248.5
XS GIS Cut Line= 4
     1757218.101       243576.15     1756910.131      243826.408
     1756740.154      243978.968     1756518.231      244157.825
#Sta/Elev= 30
       0 1476.41    79.4 1442.58   173.6 1409.65   203.4 1393.15   233.1 1373.73
   337.3 1317.97   367.1 1308.51   416.7 1300.12   436.6 1299.76   451.9 1293.47
   456.4  1292.1   466.9 1294.37   491.2 1304.57   501.1 1306.32   506.1 1304.94
     516 1298.36     521 1297.93   605.4 1297.99   615.3 1298.64   635.1 1303.96
   684.2 1304.14   718.6 1309.81   728.4 1315.57   743.2 1329.14   762.8 1342.69
   782.5  1349.5   807.1 1362.33   851.3 1392.36   885.7 1413.98   910.3 1427.28
#Mann= 3 , 0 , 0
       0      .1       0   451.9    .045       0   466.9      .1       0
#XS Ineff= 2 , 0
                          500.74         1306.24
Permanent Ineff=
       F       F
Bank Sta=451.9,466.9
XS Rating Curve= 0 ,0
Exp/Cntr=0.3,0.1

Type RM Length L Ch R = 1 ,9196.9  ,241.9,244.7,247.6
XS GIS Cut Line= 4
      1757077.52      243419.684     1756740.877      243661.231
     1756592.014      243775.427     1756386.922      243984.362
#Sta/Elev= 30
       0 1450.27    54.9 1429.65   119.8 1410.02   164.7  1391.4   199.7 1373.13
   229.6 1359.38   284.5 1339.19   309.5  1331.1   334.5 1325.13   389.4 1308.86
   404.4 1305.92   434.1 1296.79   468.6 1295.26     493 1282.26   493.3  1282.1
   498.3  1282.5     508 1285.92     523 1291.18     602 1293.57   611.9 1294.78
   621.8 1298.25   631.7 1299.52   686.3 1300.03   701.2 1300.92   711.1 1303.13
     731 1312.87   750.8 1325.49   810.4 1360.21   840.1 1383.36   894.7 1421.59
#Mann= 3 , 0 , 0
       0      .1       0     493    .045       0     508      .1       0
Bank Sta=493,508
XS Rating Curve= 0 ,0
Exp/Cntr=0.3,0.1

Type RM Length L Ch R = 1 ,8952.2  ,483.5,484.6,485.8
XS GIS Cut Line= 3
     1756946.508      243273.734      1756406.27      243587.443
     1756144.268      243703.866
#Sta/Elev= 30
       0 1518.34      10  1514.8      35 1496.57      80 1469.15     110 1448.26
   129.9 1440.77   174.9 1409.38   219.9 1380.15   269.9 1351.69   314.9  1328.7
   344.8 1309.73   369.8 1291.44   379.8 1289.44   419.8    1290   443.5 1282.51
   449.8 1280.66   458.5 1281.49   469.8 1283.26   489.8 1290.06   499.8 1291.77
   624.7 1291.17   644.5  1294.7   679.1 1294.19   713.7 1303.35   738.4 1314.81
   758.2 1321.36   832.3 1339.99   871.9  1345.2   896.6  1343.8   911.4 1337.67
#Mann= 3 , 0 , 0
       0      .1       0   443.5    .045       0   458.5      .1       0
Bank Sta=443.5,458.5
XS Rating Curve= 0 ,0
Exp/Cntr=0.3,0.1

Type RM Length L Ch R = 1 ,8467.6  ,288.9,288.5,288
XS GIS Cut Line= 4
     1756703.664      242873.541     1756468.193      243003.746
     1756198.446      243143.271     1755920.533      243310.307
#Sta/Elev= 30
       0 1448.59    19.9 1444.46    69.8  1430.2    99.7 1417.81   144.5 1392.75
   199.3  1353.8   239.2 1335.43     289 1321.12   303.9 1315.15   333.8 1305.96
   353.7 1303.54   378.6 1296.58   383.6 1294.64   403.5 1282.38   433.4 1280.46
   446.2 1274.95   453.3 1271.14   461.2 1272.82   483.2 1280.45   488.1 1280.81
   627.6 1282.18   647.6  1285.5   657.6 1288.89   707.5 1290.24   732.4 1298.46
   747.4 1306.39   772.3 1316.36   822.2 1333.36   862.1 1334.73     897 1333.96
#Mann= 3 , 0 , 0
       0      .1       0   446.2    .045       0   461.2      .1       0
Bank Sta=446.2,461.2
XS Rating Curve= 0 ,0
Exp/Cntr=0.3,0.1

Type RM Length L Ch R = 1 ,8179.1  ,437.7,436.4,435.2
XS GIS Cut Line= 4
     1756568.784      242630.123     1756235.152      242798.644
     1755918.937      242970.215     1755780.026      243054.839
#Sta/Elev= 30
       0 1416.23    54.8 1395.62    79.7 1384.46   119.6 1373.98   164.5 1355.04
   254.2 1323.29     289 1308.67     304 1306.64   328.9 1310.17   338.9 1308.84
   368.8 1294.02   383.8 1285.05   398.8 1278.39   408.8 1276.36   428.7 1275.58
   437.1 1272.67   443.7 1270.04   448.7 1269.43   452.1 1270.11   468.7 1274.04
   478.7 1275.23   578.6 1276.41   638.6  1281.8   658.6 1286.44   678.6 1288.96
   743.4    1294     773 1301.93   792.7  1309.2   827.2 1319.48   896.2 1346.73
#Mann= 3 , 0 , 0
       0      .1       0   437.1    .045       0   452.1      .1       0
Bank Sta=437.1,452.1
XS Rating Curve= 0 ,0
Exp/Cntr=0.3,0.1

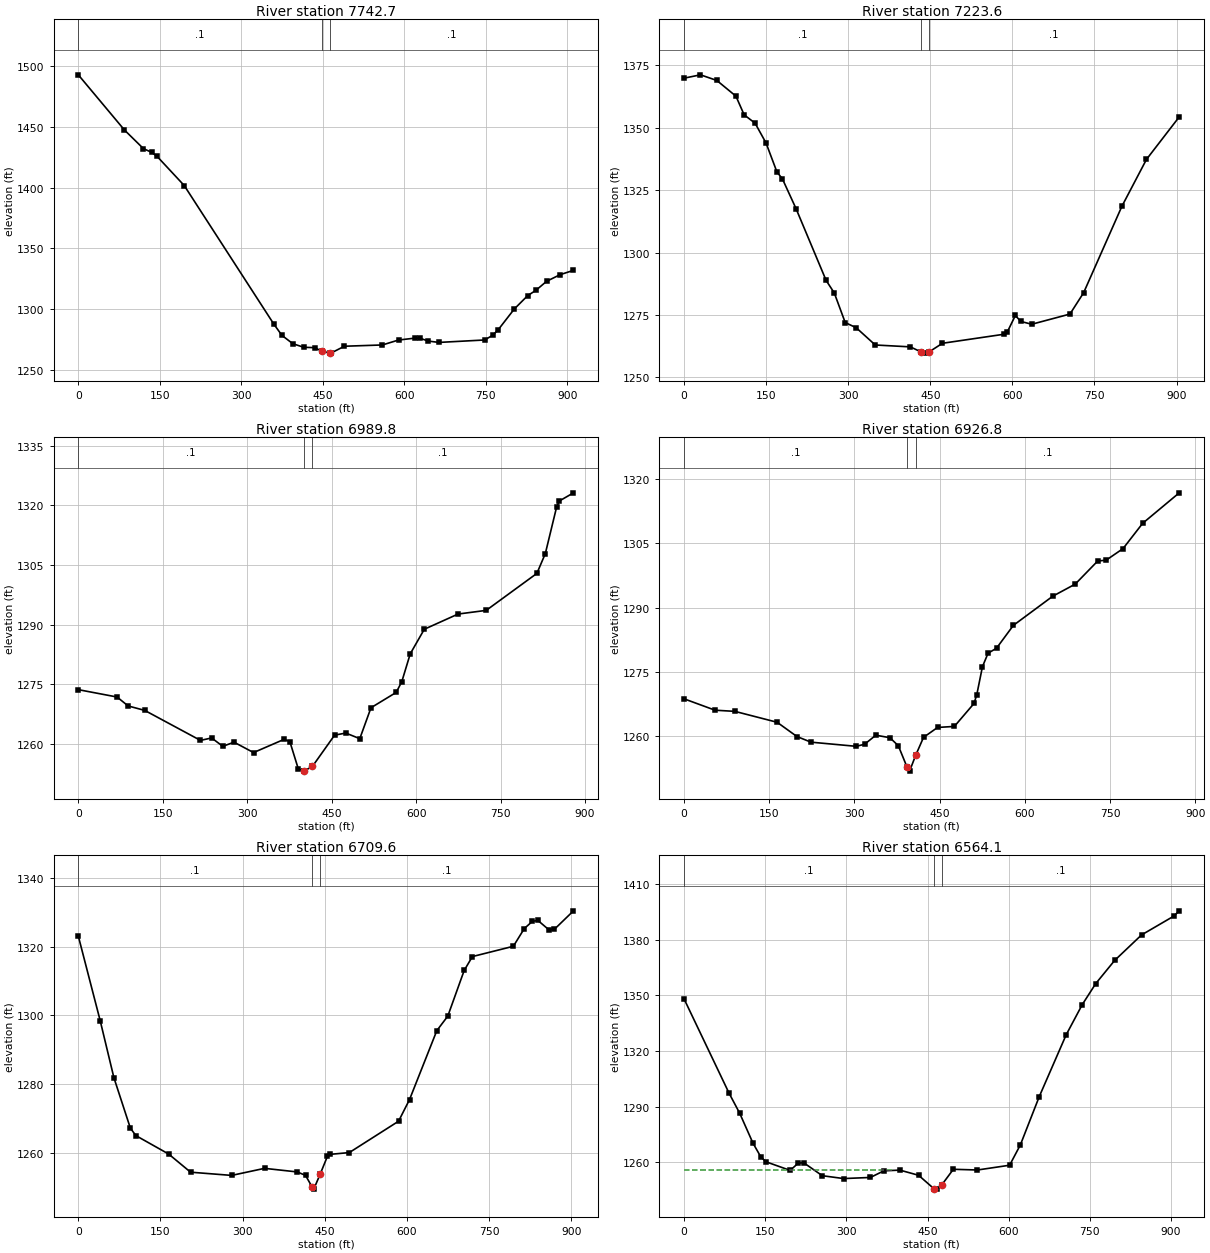
Type RM Length L Ch R = 1 ,7742.7  ,520.1,519.1,518
XS GIS Cut Line= 4
     1756345.289      242226.287     1756025.113      242411.194
      1755876.25      242502.958     1755543.802      242657.238
#Sta/Elev= 30
       0 1492.72    84.9 1447.32   119.9 1431.98   134.9 1428.97   144.9 1425.65
   194.9 1401.63   359.7 1287.66   374.7 1278.34   394.7  1271.5   414.7 1268.57
   434.7 1268.25   447.8 1265.49   462.8 1263.77   464.7 1263.75   489.6 1269.42
   559.5 1270.47   589.2 1274.53   618.9 1276.06   628.8    1276   643.7 1273.68
   663.5 1272.56   747.7 1274.57   762.5 1278.47   772.4 1282.89   802.2 1300.06
   826.9 1311.09   841.8 1315.36   861.6 1322.84   886.4 1328.28   911.1 1331.86
#Mann= 3 , 0 , 0
       0      .1       0   447.8    .045       0   462.8      .1       0
Bank Sta=447.8,462.8
XS Rating Curve= 0 ,0
Exp/Cntr=0.3,0.1

Type RM Length L Ch R = 1 ,7223.6  ,236.3,233.9,231.5
XS GIS Cut Line= 4
     1756064.234      241758.339     1755754.761      241968.997
     1755609.181      242068.094     1755307.284      242253.816
#Sta/Elev= 30
       0 1369.89      30 1371.23    59.9 1368.97    94.8 1362.67   109.8  1355.2
   129.8 1351.84   149.8 1343.91   169.7 1332.31   179.7 1329.54   204.6 1317.62
   259.6 1288.83   274.5 1283.82   294.5 1271.94   314.5 1269.89   349.4 1262.96
   413.5 1262.21   432.1 1260.28   442.8  1259.7   447.1 1260.09   472.2 1263.65
   585.4 1267.29   590.4 1268.05   605.4 1274.78   615.4  1272.4   635.3 1271.27
   705.2 1275.36   730.2 1283.92   800.1 1318.55     845 1337.34   904.9 1354.38
#Mann= 3 , 0 , 0
       0      .1       0   432.1    .045       0   447.1      .1       0
Bank Sta=432.1,447.1
XS Rating Curve= 0 ,0
Exp/Cntr=0.3,0.1

Type RM Length L Ch R = 1 ,6989.8  ,63.3,62.9,62.5
XS GIS Cut Line= 4
     1755877.334      241562.348     1755751.413      241656.789
     1755452.351      241910.598     1755210.346      242134.895
#Sta/Elev= 30
       0  1273.7    68.9 1271.85    88.5 1269.61     118 1268.49     217 1260.96
   236.8 1261.57   256.7 1259.47   276.6 1260.51   311.3  1257.9   365.9 1261.24
   375.9  1260.6   390.8  1253.8   400.7 1253.24   400.9 1253.25   415.9 1254.43
   455.3 1262.28   475.2  1262.8     500 1261.39   519.9 1269.16   564.6    1273
   574.6 1275.69   589.6 1282.69   614.6 1288.87   674.6 1292.69   724.6 1293.61
   814.6  1302.9   829.6 1307.88   849.6 1319.55   854.6 1321.09   879.6 1323.13
#Mann= 3 , 0 , 0
       0      .1       0   400.9    .045       0   415.9      .1       0
#XS Ineff= 2 , 0
          365.98 1261.22
Permanent Ineff=
       F       F
Bank Sta=400.9,415.9
XS Rating Curve= 0 ,0
Exp/Cntr=0.3,0.1

Type RM Length L Ch R = 1 ,6926.8  ,223.5,217.2,210.9
XS GIS Cut Line= 4
     1755779.297      241474.373     1755547.514      241746.672
     1755432.553      241847.605     1755156.328       242080.72
#Sta/Elev= 30
       0 1268.69    54.6 1266.03    89.4 1265.76   163.9 1263.21   198.7 1259.88
   223.5 1258.56     303 1257.59   317.9 1258.07   337.7 1260.19   362.5  1259.6
   377.3 1257.72   392.9 1252.65   397.1 1251.79   407.9  1255.5   421.7 1259.68
   446.4    1262     476 1262.24   510.6 1267.61   515.5 1269.67   525.4 1276.18
   535.3 1279.35   550.2 1280.52   579.9 1285.86   649.2 1292.67   688.8  1295.5
   728.4  1300.9   743.3  1301.1     773  1303.8   807.6 1309.72     872 1316.84
#Mann= 3 , 0 , 0
       0      .1       0   392.9    .045       0   407.9      .1       0
#XS Ineff= 2 , 0
          337.94 1260.16
Permanent Ineff=
       F       F
Bank Sta=392.9,407.9
XS Rating Curve= 0 ,0
Exp/Cntr=0.3,0.1

Type RM Length L Ch R = 1 ,6709.6  ,141.5,145.5,149.5
XS GIS Cut Line= 4
     1755641.232      241308.538     1755428.741       241513.16
     1755269.372      241761.067     1755068.685      242003.072
#Sta/Elev= 30
       0 1323.14      40 1298.44      65 1281.84      95 1267.15     105 1264.96
     165 1259.57     205 1254.28     280 1253.34     340  1255.4   399.9 1254.35
   414.9 1253.34   426.4  1250.1   429.9 1249.34   441.4 1253.63   454.8 1258.89
   459.8 1259.48   494.8    1260   584.7 1269.14   604.7 1275.44   654.6 1295.57
   674.6 1299.79   704.5  1313.1   719.5 1317.16   794.3 1320.16   814.3 1325.33
   829.2 1327.46   839.2 1327.69   859.2 1324.97   869.2 1325.11   904.1  1330.5
#Mann= 3 , 0 , 0
       0      .1       0   426.4    .045       0   441.4      .1       0
Bank Sta=426.4,441.4
XS Rating Curve= 0 ,0
Exp/Cntr=0.3,0.1

Type RM Length L Ch R = 1 ,6564.1  ,247.6,248.3,249
XS GIS Cut Line= 4
     1755523.103      241181.091     1755439.802      241325.235
     1755171.023      241615.302      1754956.73      241896.088
#Sta/Elev= 30
       0 1348.15    83.2 1297.25   102.8 1286.46   127.3 1270.35     142 1262.81
   151.8 1260.21   196.1  1255.6     211 1259.53   220.9 1259.78   255.5 1252.74
     295  1251.2   344.4  1251.8   369.2 1255.37   398.8 1255.76   433.4 1252.98
   461.5 1245.81     468  1245.5   476.5 1247.88   497.7 1256.21   542.2 1255.82
   601.7  1258.4   621.6 1269.41   656.5 1295.45   706.2 1328.76     736  1345.1
   760.9 1356.42   795.8  1368.9   845.5 1382.66   905.2 1392.82   915.2 1395.67
#Mann= 3 , 0 , 0
       0      .1       0   461.5    .045       0   476.5      .1       0
#XS Ineff= 2 , 0
          386.29 1256.08
Permanent Ineff=
       F       F
Bank Sta=461.5,476.5
XS Rating Curve= 0 ,0
Exp/Cntr=0.3,0.1

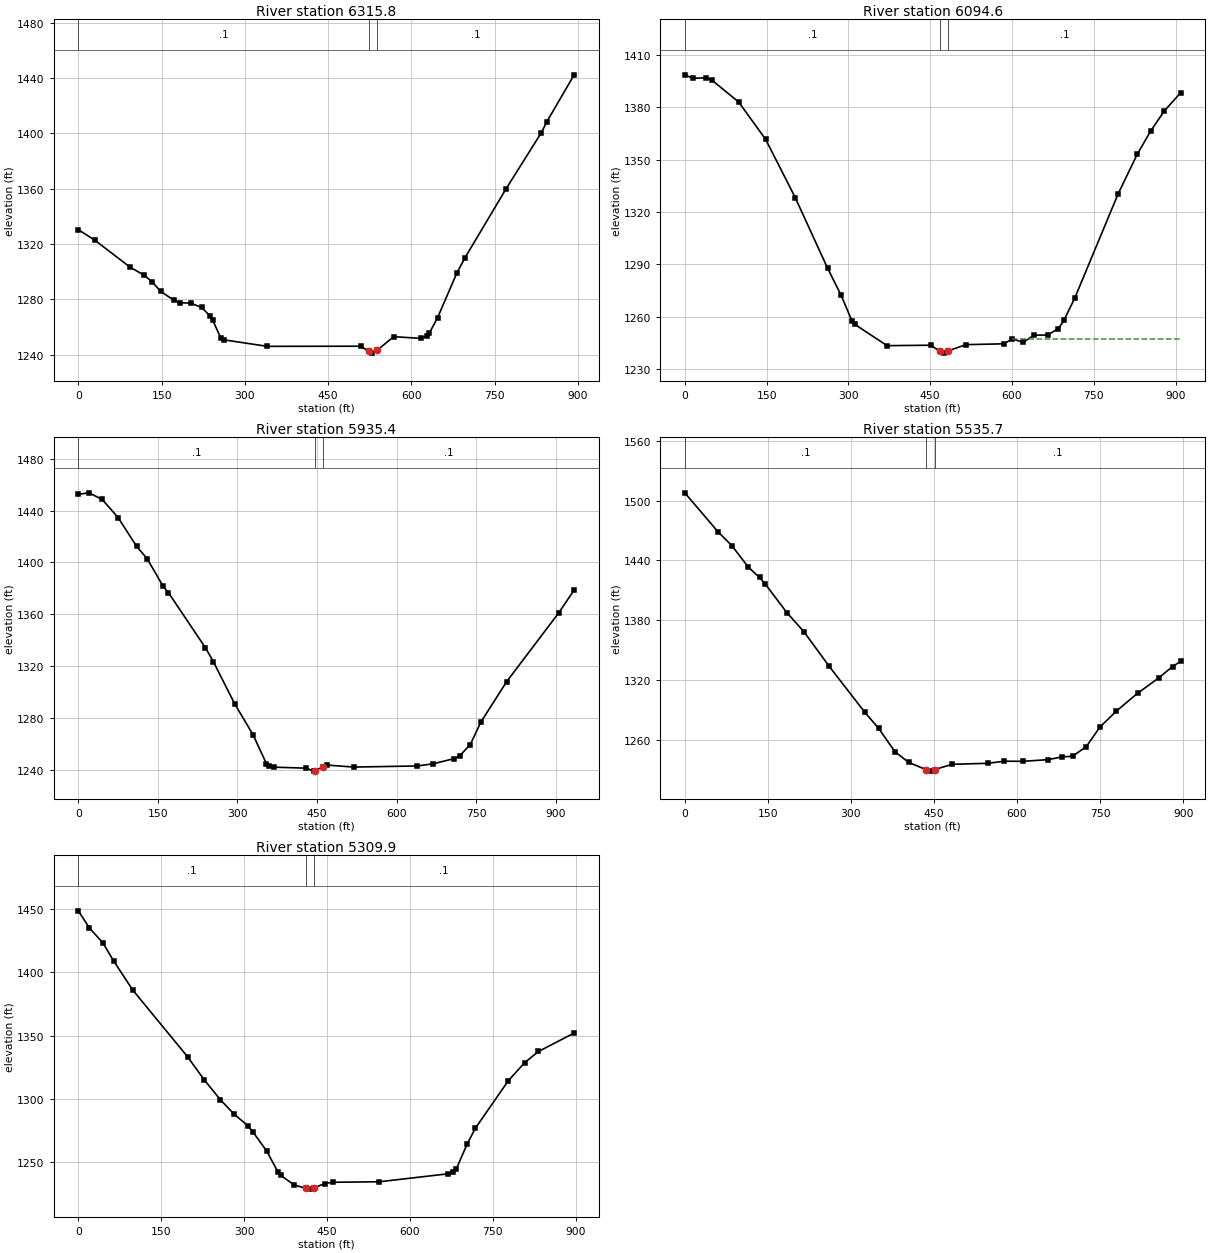
Type RM Length L Ch R = 1 ,6315.8  ,223,221.2,219.3
XS GIS Cut Line= 4
     1755421.572      241023.469     1755215.601       241215.07
     1754923.409      241510.455     1754779.709      241644.575
#Sta/Elev= 30
       0 1330.41    29.6 1322.82    93.8 1303.16   118.4 1297.57   133.2 1292.66
   148.1 1285.84   172.7  1279.3   182.6 1277.64   202.4 1277.27   222.1 1274.22
   236.9 1268.24   241.8 1265.27   256.6 1252.17   261.6 1250.82   340.7 1246.08
   508.8 1246.18   523.4 1242.45   528.6 1241.18   538.4 1243.27   568.2 1253.08
   617.7 1251.82   627.6 1253.44   632.5 1255.69   647.3 1266.77     682 1299.06
   696.8 1310.18   770.5  1359.8   834.4 1400.62   844.2 1408.46   893.4 1442.32
#Mann= 3 , 0 , 0
       0      .1       0   523.4    .045       0   538.4      .1       0
Bank Sta=523.4,538.4
XS Rating Curve= 0 ,0
Exp/Cntr=0.3,0.1

Type RM Length L Ch R = 1 ,6094.6  ,154.8,159.2,163.6
XS GIS Cut Line= 4
     1755348.125      240873.381     1755094.254      241085.739
     1754787.692      241371.544     1754663.151      241470.538
#Sta/Elev= 30
       0 1398.52    14.8 1396.53    39.5 1396.82    49.4 1395.56    98.8 1382.93
   148.2 1361.56   202.5 1328.21   261.8 1287.74   286.5 1272.34   306.3 1257.68
   311.2 1255.67   370.9 1243.36   450.7 1243.61     468 1240.13   475.7 1239.08
     483  1240.4   515.6 1243.94   585.4 1244.42   600.4 1247.31   620.4 1245.23
   640.3 1249.35   665.3 1249.45   685.2 1253.14   695.2 1257.86   715.2 1270.71
   794.8 1330.46   829.6 1352.98   854.5 1366.46   879.4 1377.85   909.2 1388.25
#Mann= 3 , 0 , 0
       0      .1       0     468    .045       0     483      .1       0
#XS Ineff= 2 , 0
                          600.22         1247.28
Permanent Ineff=
       F       F
Bank Sta=468,483
XS Rating Curve= 0 ,0
Exp/Cntr=0.3,0.1

Type RM Length L Ch R = 1 ,5935.4  ,402.2,399.7,397.2
XS GIS Cut Line= 3
     1755287.536      240754.627     1754704.665       241224.65
     1754521.214      241254.263
#Sta/Elev= 30
       0 1452.68      20  1453.8    44.9 1448.71    74.9 1434.74   109.8 1412.47
   129.8 1402.88   159.7 1381.69   169.7 1376.78   239.6 1334.12   254.6 1323.33
   294.5 1290.99   329.5 1266.78   354.4 1244.73   359.4 1242.86   369.4 1241.89
   429.3 1241.13   444.3 1238.84     446 1239.07     461 1242.19   469.2  1243.5
   519.2 1241.97     639 1242.84   668.9 1244.49   708.8 1248.57   718.8 1250.63
   738.8 1259.35   758.6 1276.65   807.4 1307.97   905.3 1360.98   934.6 1378.71
#Mann= 3 , 0 , 0
       0      .1       0     446    .045       0     461      .1       0
Bank Sta=446,461
XS Rating Curve= 0 ,0
Exp/Cntr=0.3,0.1

Type RM Length L Ch R = 1 ,5535.7  ,227,225.8,224.6
XS GIS Cut Line= 4
      1755019.21      240450.262     1754727.018      240684.973
     1754473.147      240940.442     1754354.993      241049.015
#Sta/Elev= 30
       0  1507.7      60 1468.67      85 1454.78   114.9 1433.22   134.9 1422.98
   144.9  1416.7   184.9 1387.36   214.9 1368.83   259.8  1334.7   324.8 1288.18
   349.8 1272.12   379.7 1248.41   404.4 1237.81     436 1230.51   443.9 1229.09
     451 1230.68   483.3 1235.95   547.5 1236.92   577.1 1239.04   611.6 1238.92
     656  1240.6   680.7 1243.25   700.4 1244.07   725.1 1253.63   749.5  1273.1
   778.7 1288.85   817.6 1307.03   856.5 1322.65   880.8 1333.82   895.4 1338.92
#Mann= 3 , 0 , 0
       0      .1       0     436    .045       0     451      .1       0
Bank Sta=436,451
XS Rating Curve= 0 ,0
Exp/Cntr=0.3,0.1

Type RM Length L Ch R = 1 ,5309.9  ,184.4,182.6,180.8
XS GIS Cut Line= 3
     1754806.647      240255.701     1754607.927      240476.063
     1754208.521      240924.657
#Sta/Elev= 30
       0 1448.37    19.8 1435.03    44.5 1423.07    64.3 1408.56    98.9  1385.7
   197.8 1333.27   227.5 1315.33   257.2 1299.37   281.9  1288.1   306.7 1278.97
   316.6 1273.71   341.4 1258.66   361.3 1242.51   366.2 1239.74     391  1232.2
     412 1229.56   420.8 1228.96     427 1229.96   445.6 1233.37   460.5 1234.37
   544.9 1234.77     669 1241.03     679 1242.49   683.9 1244.66   703.8 1264.61
   718.7 1277.05   778.2 1314.43     808 1328.73   832.8 1337.47   897.4 1352.04
#Mann= 3 , 0 , 0
       0      .1       0     412    .045       0     427      .1       0
Bank Sta=412,427
XS Rating Curve= 0 ,0
Exp/Cntr=0.3,0.1