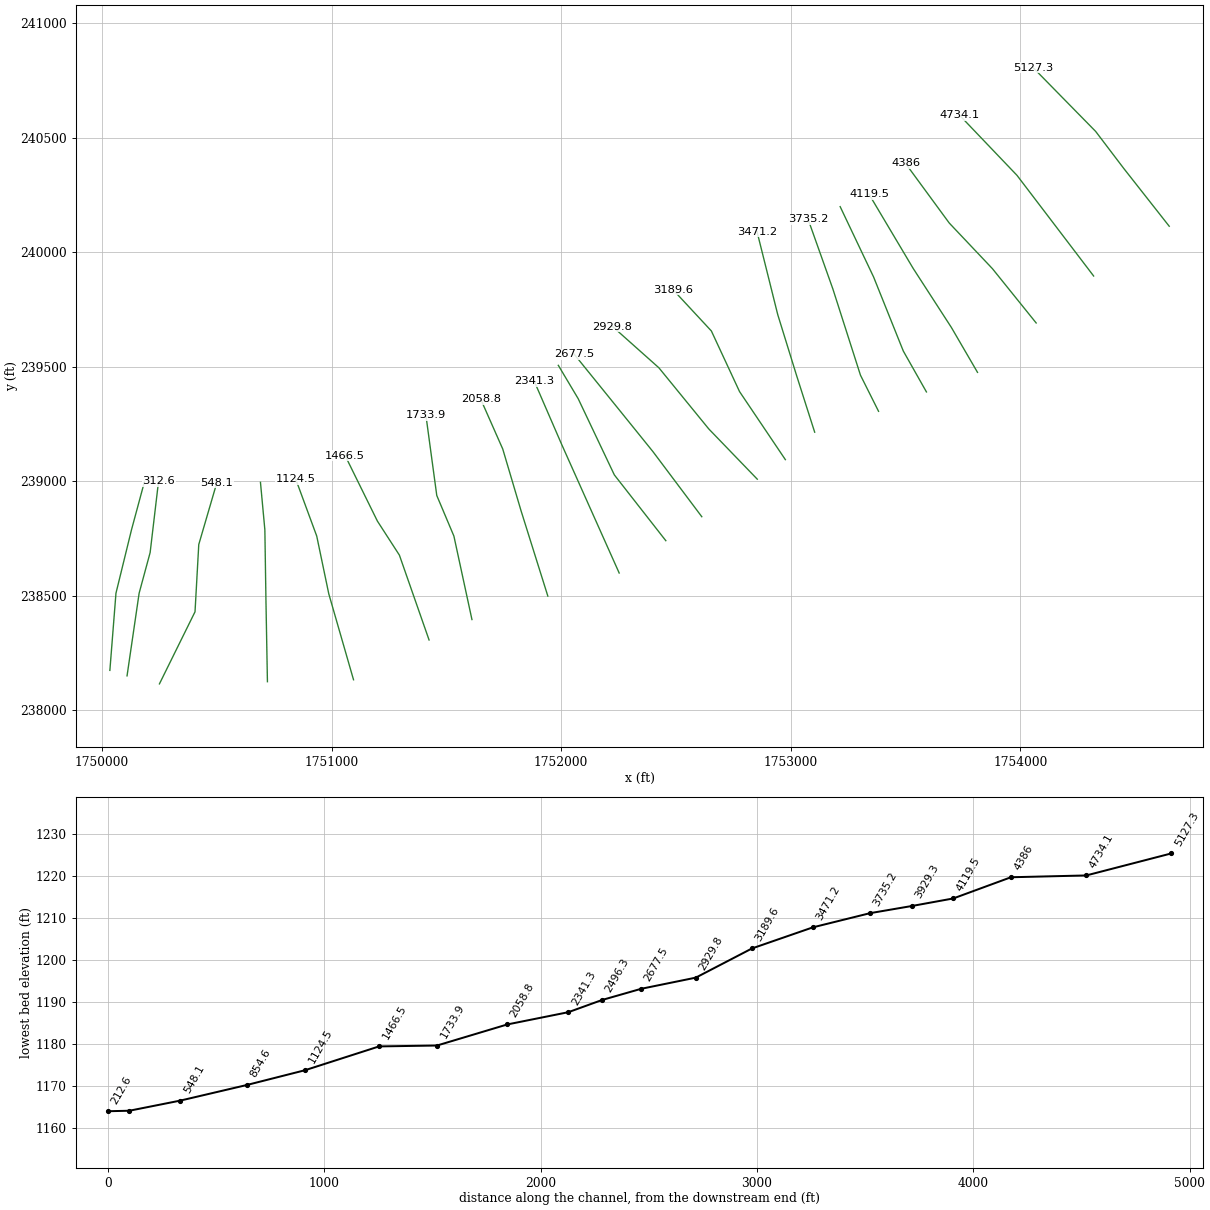
HEC-RAS study BigCubCr.prj: BigCubCr

--- BigCubCr.g01 (geometry) --- (continued)

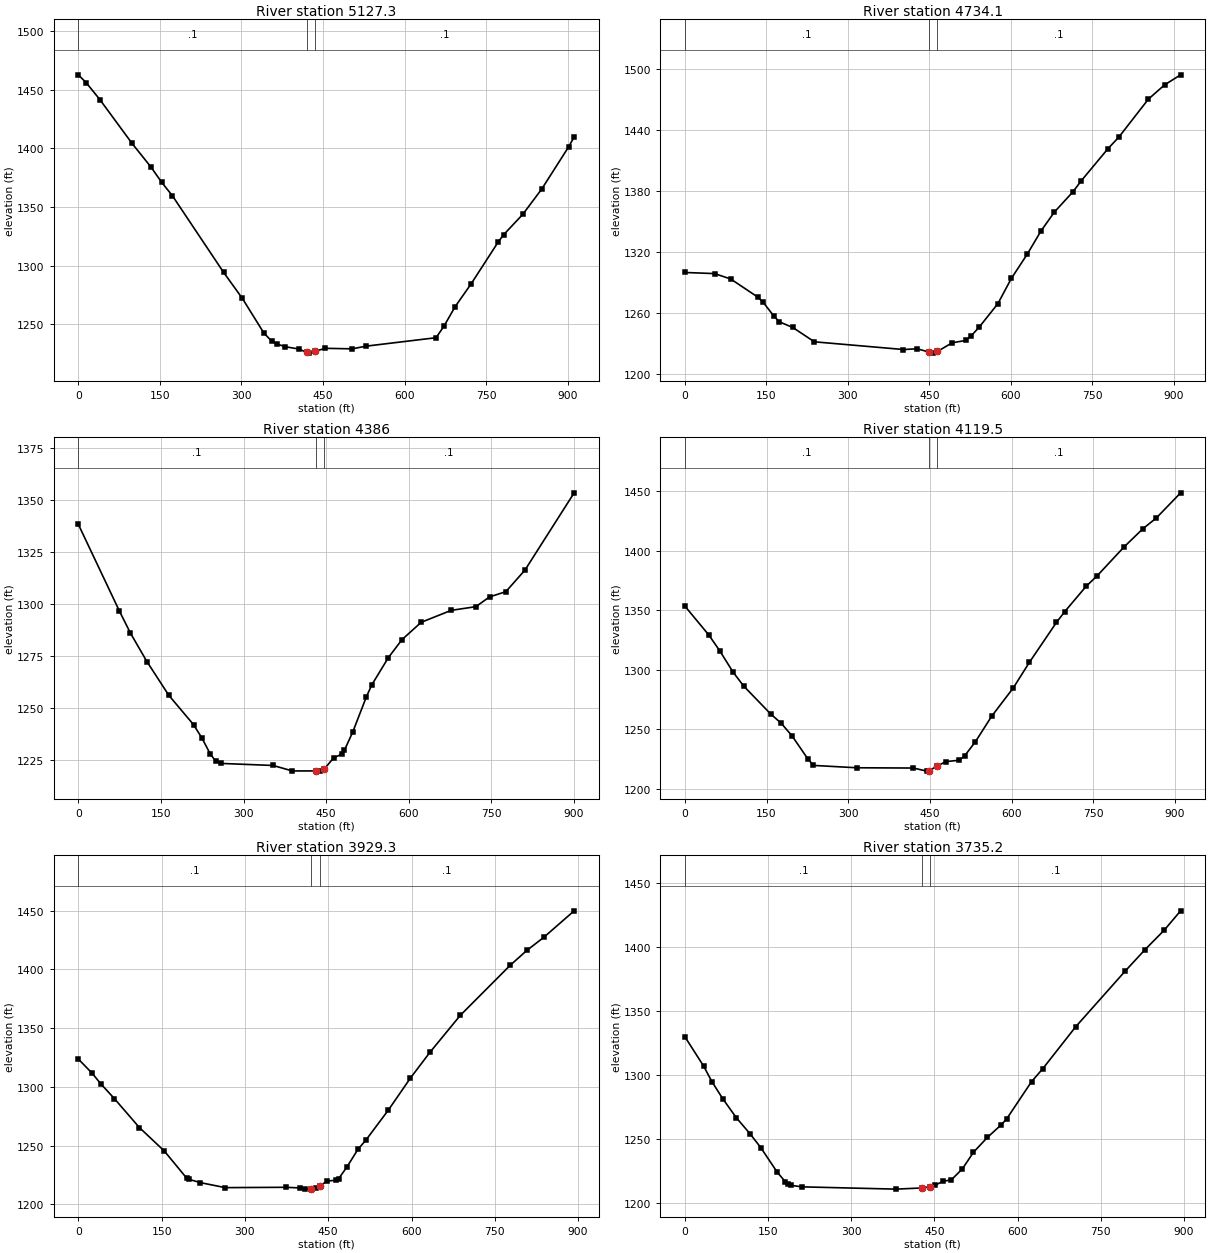
Type RM Length L Ch R = 1 ,5127.3  ,393.2,393.3,393.3
XS GIS Cut Line= 4
     1754648.657      240113.339      1754450.23      240366.108
     1754328.225      240527.139     1754056.552      240804.623
#Sta/Elev= 30
       0 1462.56    14.8 1455.68    39.6 1441.47    98.9 1404.05   133.5 1384.03
   153.3 1370.94     173 1359.51     267 1294.33   301.6 1272.07   341.1 1242.61
   355.8  1235.5   365.7 1233.14   380.5 1230.88   405.1 1228.97   420.4 1226.01
   424.8 1225.43   435.4 1227.08   454.4 1229.52   503.7 1229.09   528.4 1231.33
   657.8 1238.57   672.7 1248.68   692.6 1264.85   722.5 1284.63   772.3 1320.31
   782.3 1326.47   817.1  1343.6     852  1365.2   901.8 1401.35   911.7 1409.69
#Mann= 3 , 0 , 0
       0      .1       0   420.4    .045       0   435.4      .1       0
Bank Sta=420.4,435.4
XS Rating Curve= 0 ,0
Exp/Cntr=0.3,0.1

Type RM Length L Ch R = 1 ,4734.1  ,345.6,348,350.5
XS GIS Cut Line= 3
     1754319.405      239896.153     1753985.648      240335.342
     1753736.538      240596.623
#Sta/Elev= 30
       0 1299.66    54.7 1298.56    84.5 1293.23   134.2 1275.45   144.1 1270.37
     164 1256.65   173.9 1251.05   198.8 1245.43   238.5 1231.32   402.5 1223.72
   427.4 1224.46   449.9 1221.22   457.2 1220.17   464.9  1221.8     492 1230.33
   516.8 1232.65   526.8 1237.03   541.7 1245.68   576.3 1268.96   601.1 1293.85
   630.7 1318.01   655.5 1340.49   680.2 1359.16   714.8  1379.4   729.6 1389.95
   779.1 1421.81   798.9 1433.08   853.3  1470.5     883  1484.5   912.6 1494.45
#Mann= 3 , 0 , 0
       0      .1       0   449.9    .045       0   464.9      .1       0
Bank Sta=449.9,464.9
XS Rating Curve= 0 ,0
Exp/Cntr=0.3,0.1

Type RM Length L Ch R = 1 ,4386    ,270.7,266.5,262.4
XS GIS Cut Line= 4
     1754069.028      239691.184     1753878.671      239928.024
     1753690.527      240127.236     1753500.169      240387.317
#Sta/Elev= 30
       0 1338.47    74.7 1296.68    94.6 1286.15   124.5 1272.45   164.4 1256.17
   209.2 1242.08   224.2 1235.75   239.1 1228.22   249.1 1224.58     259 1223.45
   353.7 1222.46   388.6 1219.82   430.9 1219.84   438.4 1219.74   445.9 1220.56
   463.3 1226.06   478.2 1227.94   483.2 1229.86   498.2 1238.54   523.1 1255.58
     533 1261.34   562.9 1274.36   587.8 1283.05   622.5 1291.34     677 1297.09
   721.7 1298.86   746.5 1303.55   776.2 1306.08   810.9 1316.47   900.2 1353.63
#Mann= 3 , 0 , 0
       0      .1       0   430.9    .045       0   445.9      .1       0
Bank Sta=430.9,445.9
XS Rating Curve= 0 ,0
Exp/Cntr=0.3,0.1

Type RM Length L Ch R = 1 ,4119.5  ,194.6,190.2,185.9
XS GIS Cut Line= 4
     1753813.559      239475.646      1753699.87      239671.362
     1753533.195      239929.471     1753340.873      240253.271
#Sta/Elev= 30
       0 1353.62    44.3 1329.09      64 1316.04    88.6 1297.99   108.2 1286.21
   157.4 1262.89   177.1  1254.9   196.8 1244.37   226.3  1224.7   236.2 1219.49
   315.5 1217.51   419.6 1217.28   444.4 1214.68   447.6 1214.77   462.6 1218.78
   479.1 1222.69   503.8 1223.83   513.8 1227.57   533.6 1239.49   563.3 1260.84
     603 1284.71   632.7  1306.3   682.2 1339.77   697.1 1348.68   736.8 1370.22
   756.6 1378.84   806.1  1403.2   840.8 1418.56   865.6 1427.68   910.2 1448.85
#Mann= 3 , 0 , 0
       0      .1       0   447.6    .045       0   462.6      .1       0
Bank Sta=447.6,462.6
XS Rating Curve= 0 ,0
Exp/Cntr=0.3,0.1

Type RM Length L Ch R = 1 ,3929.3  ,195.7,194.1,192.5
XS GIS Cut Line= 4
     1753591.079      239390.208     1753490.371      239568.531
      1753360.88      239891.925     1753215.284      240198.858
#Sta/Elev= 30
       0 1323.62      25 1311.48      40 1302.77    64.9 1289.94   109.9 1265.33
   154.8 1245.36   194.8  1222.4   199.8 1221.16   219.7 1218.44   264.5 1214.16
     374 1214.45   398.9 1213.91   408.8 1212.89   419.8 1213.42   428.7 1214.27
   434.8 1215.86   448.6 1219.73   463.6  1220.5   468.6 1221.68   483.5 1231.59
   503.4 1246.65   518.3 1254.89   558.2 1280.11   598.1 1307.47   633.1  1329.3
     688 1360.88     778 1403.56   807.9 1416.16   837.9  1427.1   892.9 1449.78
#Mann= 3 , 0 , 0
       0      .1       0   419.8    .045       0   434.8      .1       0
Bank Sta=419.8,434.8
XS Rating Curve= 0 ,0
Exp/Cntr=0.3,0.1

Type RM Length L Ch R = 1 ,3735.2  ,264.1,263.9,263.7
XS GIS Cut Line= 4
     1753382.522      239305.605     1753303.822      239463.007
     1753183.803      239838.803      1753075.59      240143.768
#Sta/Elev= 30
       0 1330.14    34.2 1306.98    48.9 1295.02    68.4 1281.72    92.9 1266.88
   117.3 1254.54   136.9 1243.62   166.2 1224.68     181 1217.05     186 1215.12
     191 1214.17   210.9 1212.95   380.7 1211.17   427.2 1212.07   442.2 1213.09
   450.6 1214.06   465.6 1217.27   480.6  1218.4   500.6 1227.01   520.5 1239.91
   545.5 1251.45   570.5 1261.33   580.4 1265.96   625.2 1294.98   645.2 1304.96
   704.9 1337.84   794.5 1381.44   829.4 1397.78   864.2 1413.05   894.1 1428.28
#Mann= 3 , 0 , 0
       0      .1       0   427.2    .045       0   442.2      .1       0
Bank Sta=427.2,442.2
XS Rating Curve= 0 ,0
Exp/Cntr=0.3,0.1

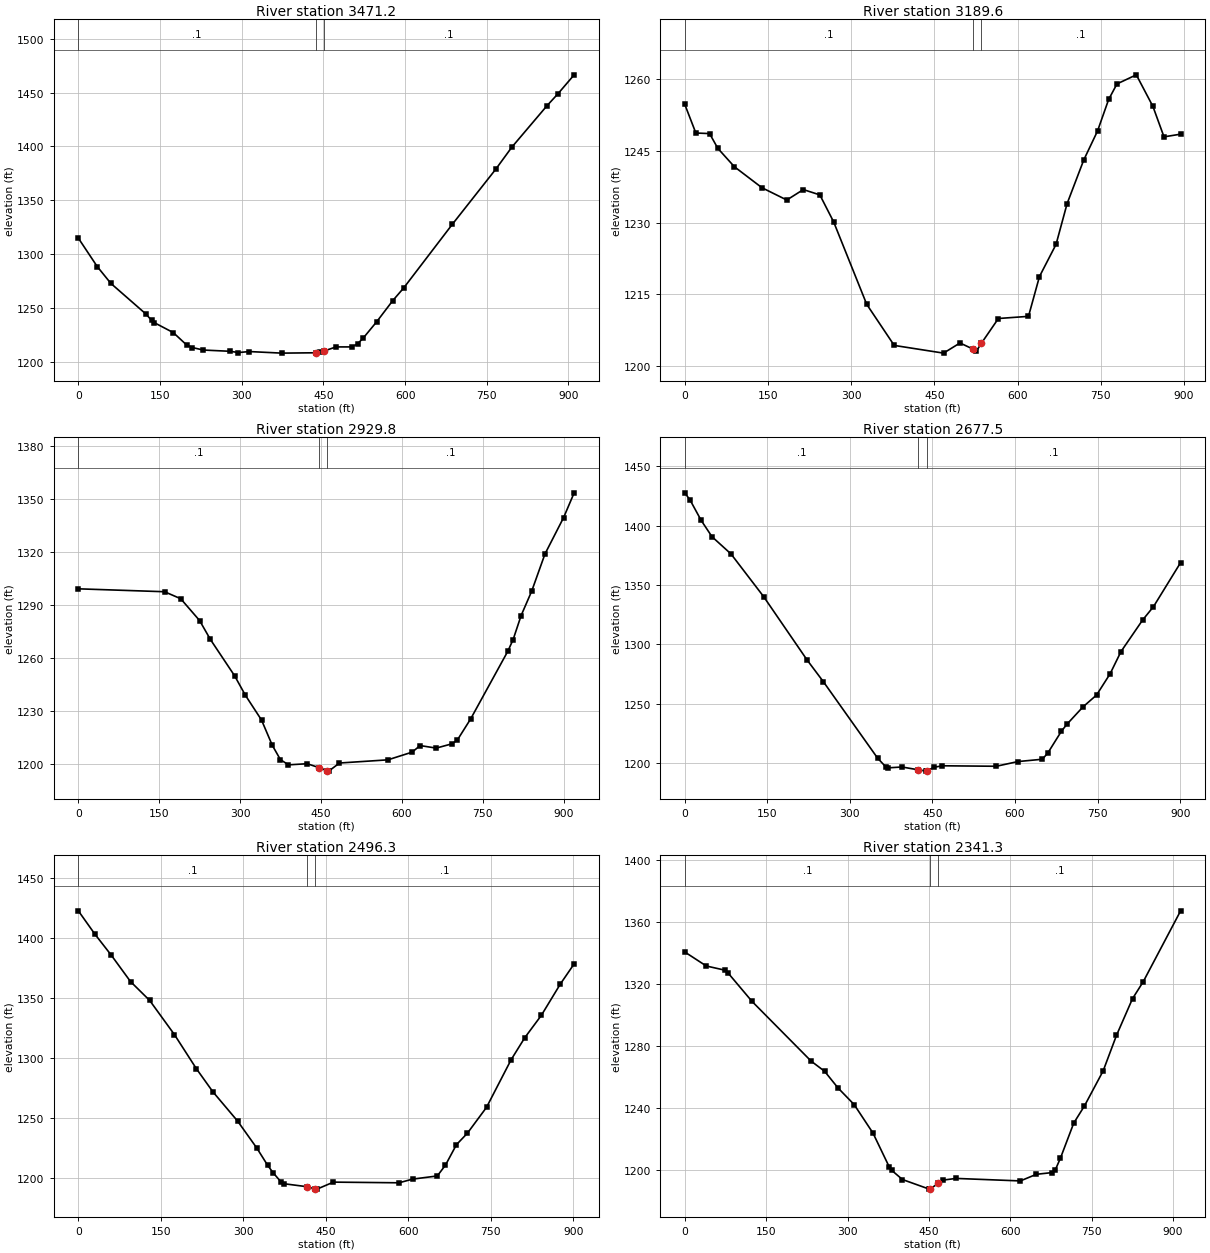
Type RM Length L Ch R = 1 ,3471.2  ,278.6,281.7,284.7
XS GIS Cut Line= 4
     1753104.285       239214.46     1753025.608      239461.313
     1752943.378      239727.589     1752853.285      240089.159
#Sta/Elev= 30
       0  1314.7    34.9 1288.13    59.8 1272.58   124.6 1243.92   134.5  1238.2
   139.5 1236.12   174.4 1226.85   199.3 1215.16   209.3 1212.99   229.2 1210.67
     279 1209.49   293.9 1208.33   313.8 1209.25   373.6 1207.79   435.7 1208.12
   443.2 1208.42   450.7 1209.67   473.1 1213.56   502.9 1213.57   512.9  1216.6
   522.8  1221.6   547.7 1236.88   577.5 1256.71   597.4 1268.38   686.8 1327.61
   766.3 1378.66   796.1 1399.33   860.7 1437.88   880.6 1448.86   910.4  1466.5
#Mann= 3 , 0 , 0
       0      .1       0   435.7    .045       0   450.7      .1       0
Bank Sta=435.7,450.7
XS Rating Curve= 0 ,0
Exp/Cntr=0.3,0.1

Type RM Length L Ch R = 1 ,3189.6  ,254,259.8,265.6
XS GIS Cut Line= 4
     1752976.549      239094.725     1752776.964      239391.707
     1752654.294      239656.217     1752487.966      239835.582
#Sta/Elev= 30
       0 1254.68    19.9 1248.71    44.7 1248.59    59.6  1245.5    89.4 1241.67
   139.2 1237.28   183.9 1234.72   213.7  1236.9   243.5 1235.79   268.4 1230.15
     328 1212.94   377.6 1204.36   466.5 1202.75   496.2 1204.87   519.9 1203.58
   525.8 1203.18   534.9 1204.83   565.4 1209.98   619.7 1210.43   639.5 1218.75
   669.4 1225.46   689.3 1233.96   719.3 1243.07   744.2 1249.14   764.2 1255.71
   779.2 1258.96   814.1 1260.86   844.1 1254.25     864 1247.91     894 1248.47
#Mann= 3 , 0 , 0
       0      .1       0   519.9    .045       0   534.9      .1       0
Bank Sta=519.9,534.9
XS Rating Curve= 0 ,0
Exp/Cntr=0.3,0.1

Type RM Length L Ch R = 1 ,2929.8  ,252.3,252.2,252.1
XS GIS Cut Line= 4
     1752854.238       239009.39     1752642.844      239228.846
     1752425.696      239495.491     1752223.847      239675.642
#Sta/Elev= 30
       0 1299.17   159.8 1297.52   189.8 1293.55   224.8 1281.17   244.8 1270.45
   289.7 1249.85   309.7 1238.78   339.6 1224.75   359.5 1210.44   374.5 1202.36
   389.4 1199.34   424.3 1199.98   446.3 1197.74   461.3 1195.96   464.2 1195.78
   484.1 1200.38   573.8 1202.18   618.7 1206.54   633.6 1210.27   663.4 1208.84
   692.9 1211.29   702.7 1213.48   727.3 1225.42   796.2 1263.82     806 1270.42
   820.8 1284.03   840.4 1297.86     865 1318.94   899.5 1339.56   919.1 1353.61
#Mann= 3 , 0 , 0
       0      .1       0   446.3    .045       0   461.3      .1       0
Bank Sta=446.3,461.3
XS Rating Curve= 0 ,0
Exp/Cntr=0.3,0.1

Type RM Length L Ch R = 1 ,2677.5  ,186.7,181.3,175.8
XS GIS Cut Line= 4
     1752612.507      238845.644     1752399.392        239130.1
     1752258.045      239305.486     1752056.864      239554.568
#Sta/Elev= 30
       0 1427.59     9.9 1421.26    29.6 1404.48    49.4 1390.63    83.9 1376.12
   143.2 1340.18   222.2 1286.75   251.8 1268.45   350.5 1203.95   365.2 1196.71
   370.1  1195.9   394.6  1196.6   424.6 1194.21   438.7 1193.12   439.6 1193.35
   453.4 1196.41   468.1 1197.62     566 1197.22   605.3 1201.18   649.6 1203.13
   659.5 1208.32   684.1 1226.59     694 1232.46   723.5 1247.24   748.2 1257.25
   772.8 1275.16   792.5 1293.82   831.9 1320.46   851.6  1331.7   900.9 1368.82
#Mann= 3 , 0 , 0
       0      .1       0   424.6    .045       0   439.6      .1       0
Bank Sta=424.6,439.6
XS Rating Curve= 0 ,0
Exp/Cntr=0.3,0.1

Type RM Length L Ch R = 1 ,2496.3  ,155.6,155,154.4
XS GIS Cut Line= 4
     1752455.822      238740.928     1752231.525      239028.185
     1752074.123      239360.696     1751987.553      239506.292
#Sta/Elev= 30
       0 1422.44      30 1403.06    59.9 1385.47    94.9 1363.47   129.8  1347.7
   174.7 1319.31   214.7 1290.81   244.6 1271.63   289.6 1247.19   324.5 1224.74
   344.5 1210.15   354.5 1203.95   369.4 1196.01   374.4 1194.91   415.2 1192.51
   430.2 1190.67     434 1190.44   463.9 1196.28   583.2 1195.72     608 1198.79
   652.8 1201.42   667.7 1210.47   687.6 1227.48   707.5 1237.04   742.3  1258.6
   787.1 1298.36     812 1316.75   841.9 1335.22   876.8 1361.58   901.7 1378.23
#Mann= 3 , 0 , 0
       0      .1       0   415.2    .045       0   430.2      .1       0
Bank Sta=415.2,430.2
XS Rating Curve= 0 ,0
Exp/Cntr=0.3,0.1

Type RM Length L Ch R = 1 ,2341.3  ,285.5,282.4,279.4
XS GIS Cut Line= 4
     1752252.669      238599.925     1752107.241      238925.717
     1752002.577      239160.189     1751883.223      239435.778
#Sta/Elev= 30
       0 1340.76    39.6 1331.72    74.3 1328.98    79.3 1327.38   123.9 1308.84
   232.9 1270.24   257.7 1263.68   282.4 1252.92   312.2 1242.15   346.9 1223.74
   376.5 1202.13   381.5 1199.64   401.2 1193.74   450.6 1187.54   452.1 1187.66
   467.1 1191.23   475.3 1193.34     500 1194.46   618.5 1192.84     648 1197.12
   677.6 1198.25   682.5 1199.67   692.3 1207.49   716.9 1230.21   736.6 1241.28
   771.1 1263.93   795.7 1286.91   825.2  1310.6     845 1321.58   913.9 1367.36
#Mann= 3 , 0 , 0
       0      .1       0   452.1    .045       0   467.1      .1       0
Bank Sta=452.1,467.1
XS Rating Curve= 0 ,0
Exp/Cntr=0.3,0.1

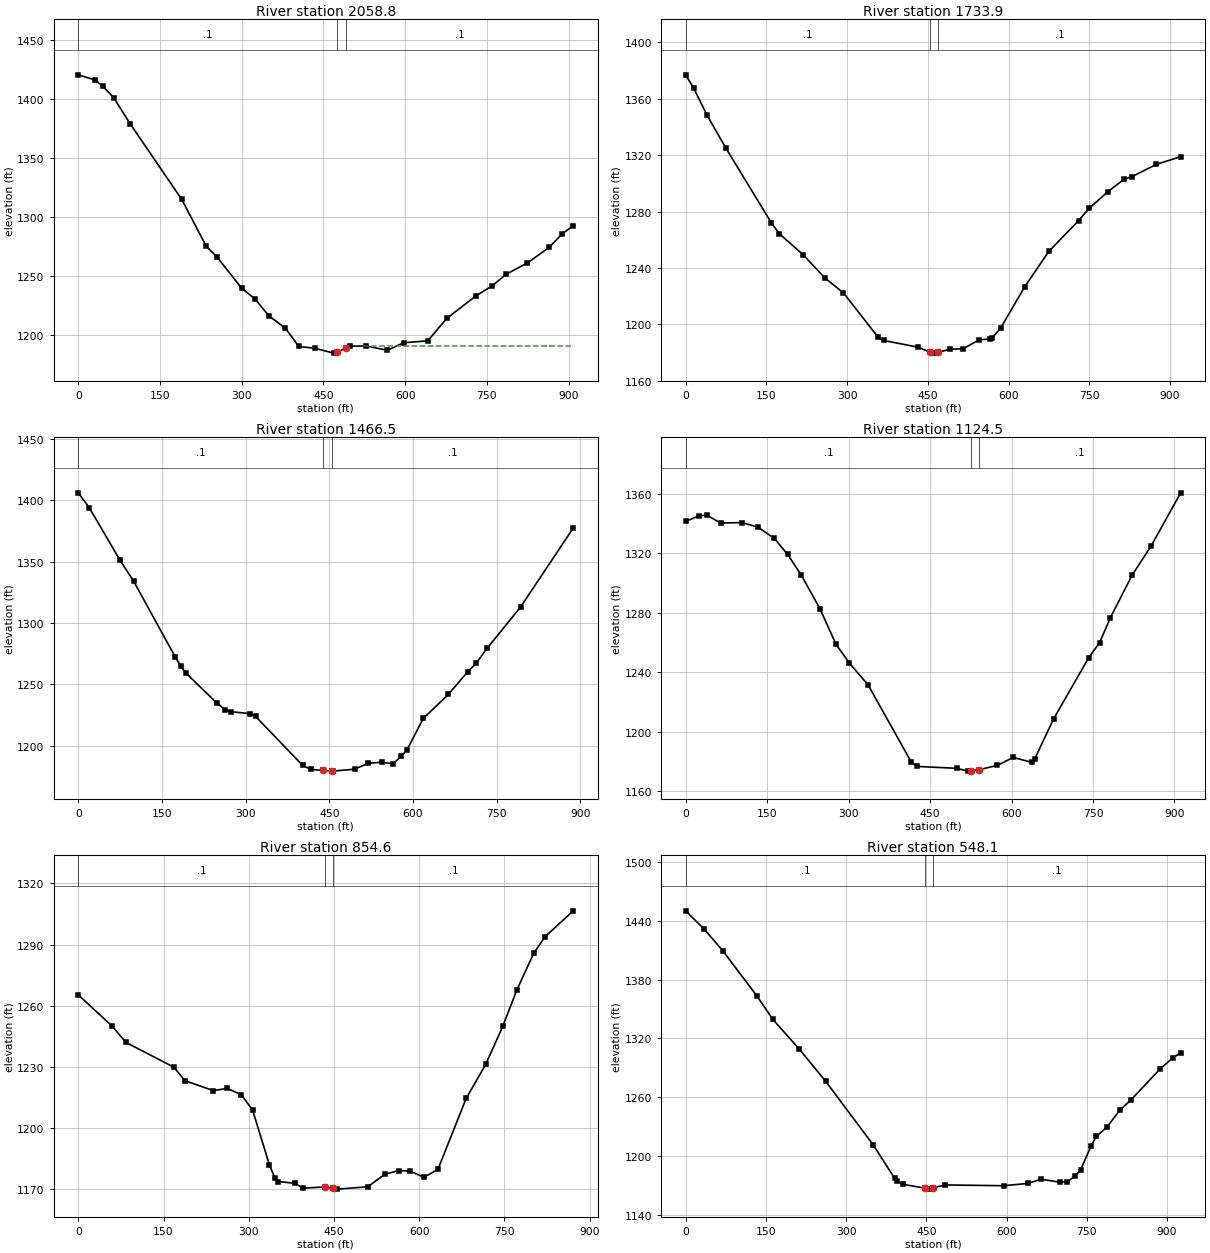
Type RM Length L Ch R = 1 ,2058.8  ,322.2,324.9,327.6
XS GIS Cut Line= 4
     1751941.903      238499.165     1751825.346       238871.19
     1751745.512      239141.029     1751649.711      239358.177
#Sta/Elev= 30
       0 1420.58      30 1416.33      45 1410.86      65 1401.22      95 1379.23
   189.9 1314.92   234.9 1275.27   254.9 1265.95   299.9 1239.67   324.9  1230.3
   349.9 1216.15   379.9 1205.91   404.7 1190.28   434.3  1188.7   468.8 1184.61
   475.7 1185.26   490.7 1189.11   498.5 1190.55   528.1 1190.68   567.6 1187.04
   597.2  1193.4   641.6 1195.03   676.2 1213.99   730.6 1233.38   760.3 1241.75
     785 1251.42   824.5 1261.06   864.1 1274.22   888.8 1285.99   908.6 1292.55
#Mann= 3 , 0 , 0
       0      .1       0   475.7    .045       0   490.7      .1       0
#XS Ineff= 2 , 0
                          523.29         1190.67
Permanent Ineff=
       F       F
Bank Sta=475.7,490.7
XS Rating Curve= 0 ,0
Exp/Cntr=0.3,0.1

Type RM Length L Ch R = 1 ,1733.9  ,263.5,267.4,271.3
XS GIS Cut Line= 4
      1751611.34      238396.754     1751532.726      238761.002
      1751458.11      238938.251     1751410.592      239289.693
#Sta/Elev= 30
       0 1377.01    14.9  1367.5    39.8 1348.31    74.5 1325.13     159 1272.14
   173.9  1264.3   218.6 1249.25   258.4 1232.96   293.1 1222.33   357.7 1190.79
   367.7 1188.57   431.8 1183.78   454.3 1180.24   461.4 1179.58   469.3 1180.24
     491 1182.29   515.6 1182.72   545.2 1189.01     565 1189.63   569.9 1190.62
   584.9 1197.19   629.9 1226.71   674.8  1251.8   729.8 1273.53   749.8 1282.38
   784.7 1294.23   814.7 1302.96   829.7 1304.88   874.6 1313.51   919.6 1318.96
#Mann= 3 , 0 , 0
       0      .1       0   454.3    .045       0   469.3      .1       0
Bank Sta=454.3,469.3
XS Rating Curve= 0 ,0
Exp/Cntr=0.3,0.1

Type RM Length L Ch R = 1 ,1466.5  ,351.2,342,333.6
XS GIS Cut Line= 4
      1751424.58      238307.564     1751295.249      238677.993
     1751199.449      238826.484     1751058.942      239112.288
#Sta/Elev= 30
       0 1406.15    19.9 1393.89    74.5 1351.47    99.3 1334.09   173.8 1272.47
   183.8 1264.86   193.7 1258.99   248.3 1234.85   263.2 1229.45   273.2 1227.86
   307.9  1226.2   317.9 1223.95   402.2 1184.06   416.9  1180.7   439.1 1179.97
   454.1 1179.41   456.2 1179.37   495.4 1180.94     520  1185.8   544.5 1186.63
   564.2 1185.35     579 1191.46     589 1196.41   618.8 1222.42   663.6 1241.88
   698.4 1260.44   713.4 1267.23   733.3 1279.63     793 1313.08   887.5 1377.46
#Mann= 3 , 0 , 0
       0      .1       0   439.1    .045       0   454.1      .1       0
Bank Sta=439.1,454.1
XS Rating Curve= 0 ,0
Exp/Cntr=0.3,0.1

Type RM Length L Ch R = 1 ,1124.5  ,272.6,269.9,266.5
XS GIS Cut Line= 4
     1751095.504      238133.968      1750987.67      238509.143
     1750935.237      238761.002     1750844.126      239008.558
#Sta/Elev= 30
       0 1341.48    24.7 1345.34    39.5  1345.6    64.2 1340.44   103.8 1340.69
   133.4  1337.6   163.1 1330.09   187.8 1319.29   212.5 1305.61   247.1 1282.88
   276.7 1258.99   301.4  1246.3     336 1231.55   415.1 1180.01     425 1176.86
   499.2 1175.57     519 1173.69   525.9 1173.87   540.9 1174.69   573.4 1177.52
   603.1 1182.87   637.7 1179.57   642.7 1181.92   677.5 1208.84   742.2    1250
   762.1 1259.98     782 1276.76   821.8 1305.27   856.7  1324.8   911.4 1360.71
#Mann= 3 , 0 , 0
       0      .1       0   525.9    .045       0   540.9      .1       0
Bank Sta=525.9,540.9
XS Rating Curve= 0 ,0
Exp/Cntr=0.3,0.1

Type RM Length L Ch R = 1 ,854.6   ,308,306.4,304.9
XS GIS Cut Line= 4
     1750720.446      238125.543      1750714.06      238476.812
     1750709.269      238788.163     1750690.109      238995.731
#Sta/Elev= 30
       0 1265.35    59.4 1250.09    84.1 1242.04   168.2 1229.92     188 1223.28
   237.5 1218.47   262.3 1219.49     287 1216.43   306.8 1208.88   336.5 1181.98
   346.4 1175.37   351.3 1173.88     381    1173   395.8 1170.63     434 1171.22
     449 1170.53   455.1 1170.15   509.5 1171.27   539.2  1177.4   563.9 1179.24
   583.6 1179.02   608.4 1175.94   633.1 1179.86   682.6 1214.58   717.3 1231.41
   747.1 1249.94   771.9  1267.8   801.7 1285.83   821.5 1293.87   871.2 1306.57
#Mann= 3 , 0 , 0
       0      .1       0     434    .045       0     449      .1       0
Bank Sta=434,449
XS Rating Curve= 0 ,0
Exp/Cntr=0.3,0.1

Type RM Length L Ch R = 1 ,548.1   ,240.2,235.5,230.8
XS GIS Cut Line= 4
     1750250.027      238116.052     1750405.042       238430.65
     1750421.355      238724.296     1750499.968      238993.764
#Sta/Elev= 30
       0 1450.15    34.6  1431.4    69.2 1409.58   133.4 1363.19     163 1339.46
   212.4 1309.18   261.8 1276.34   350.7 1211.51   390.6  1177.5   395.6 1174.38
   405.6 1171.36   448.1 1167.43   455.4 1166.44   463.1 1167.91   485.3 1170.69
     595 1169.92   639.8 1172.25   664.5 1176.53     699 1173.58   713.8 1174.05
   728.5 1179.88   738.4 1186.15   758.1 1210.52   767.9 1220.14   787.6 1229.68
   812.2 1247.22     832    1257   886.1 1288.44   910.7 1300.28   925.5 1305.32
#Mann= 3 , 0 , 0
       0      .1       0   448.1    .045       0   463.1      .1       0
Bank Sta=448.1,463.1
XS Rating Curve= 0 ,0
Exp/Cntr=0.3,0.1

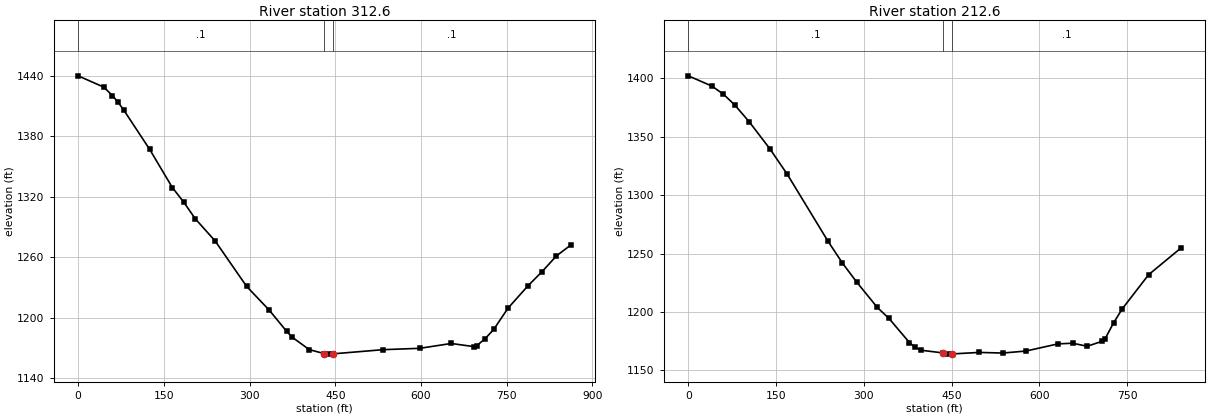
Type RM Length L Ch R = 1 ,312.6   ,99.5,100,100.6
XS GIS Cut Line= 4
     1750108.919       238151.09      1750161.61      238511.938
      1750209.51      238689.169     1750246.234      239000.521
#Sta/Elev= 30
       0 1440.19      45 1428.93      60 1420.56    69.9 1413.97    79.9 1406.14
   124.9 1367.42   164.8 1329.36   184.8 1314.79   204.8 1298.46   239.8 1276.25
   294.7 1231.33   334.7 1207.47   364.7 1186.73   374.6 1180.81   404.4 1168.49
   430.8 1164.52   439.1 1164.02   445.8 1164.29   533.4 1168.43     598 1169.79
   652.8 1174.59   692.6 1171.47   697.6 1172.41   712.5  1179.5   727.4 1188.65
   752.3 1209.64   787.1 1231.76     812 1245.94   836.9 1261.44   861.8 1272.15
#Mann= 3 , 0 , 0
       0      .1       0   430.8    .045       0   445.8      .1       0
Bank Sta=430.8,445.8
XS Rating Curve= 0 ,0
Exp/Cntr=0.3,0.1

Type RM Length L Ch R = 1 ,212.6   ,216.4,212.6,208.7
XS GIS Cut Line= 4
     1750034.124      238174.896     1750060.667      238511.786
     1750128.045      238787.424     1750185.214      238999.768
#Sta/Elev= 30
       0 1402.25    39.8 1393.54    59.6 1386.66    79.5 1377.19   104.4 1362.62
   139.2 1339.82     169 1317.97   238.5  1260.7   263.4 1241.83   288.2 1225.27
     323 1203.86   342.9 1194.44   377.8 1173.83   387.7 1169.66   397.7 1167.24
   435.1 1164.93   442.5  1163.9   450.1 1164.05   497.2 1165.37   537.1 1164.82
   576.9 1166.54   631.7 1172.68   656.7 1173.24   681.7 1170.64   706.6 1174.81
   711.6 1176.44   726.6 1190.58   741.6 1202.71   786.6 1231.92   841.6 1254.66
#Mann= 3 , 0 , 0
       0      .1       0   435.1    .045       0   450.1      .1       0
Bank Sta=435.1,450.1
XS Rating Curve= 0 ,0
Exp/Cntr=0.3,0.1

Chan Stop Cuts=-1
Use User Specified Reach Order=0